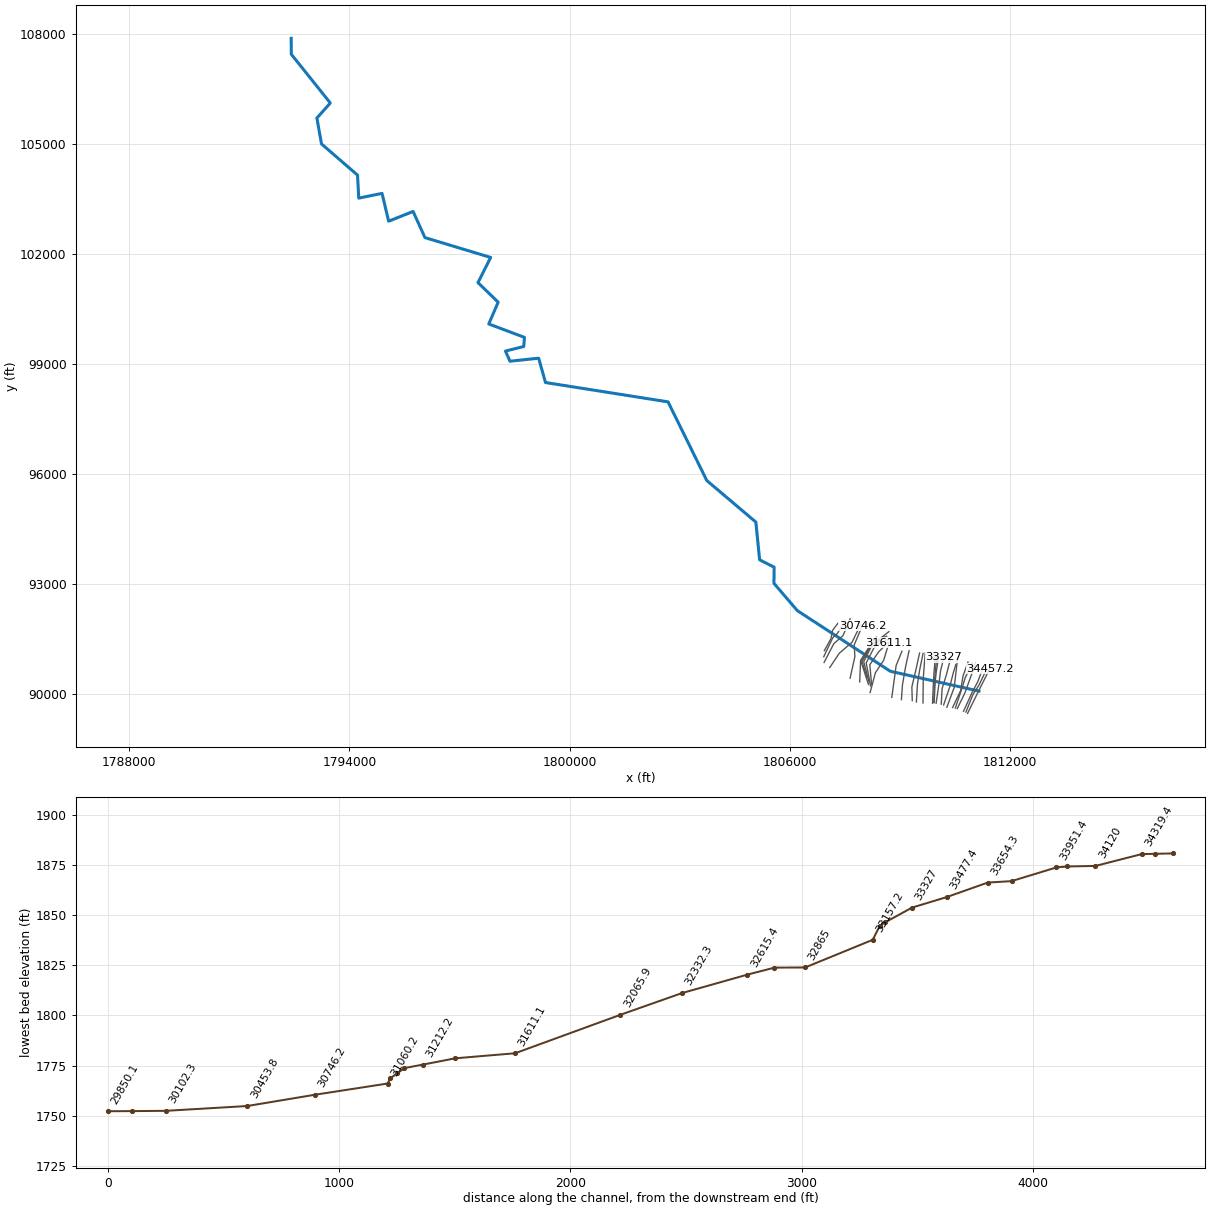
--- Big Creek.prj (project) ---

Proj Title=Big Creek
Current Plan=p01
Default Exp/Contr=0,0
English Units
Geom File=g01
Flow File=f01
Plan File=p01
BEGIN DESCRIPTION:
END DESCRIPTION:
DSS Export Rating Curves= 0
DSS Export Rating Curve Sorted= 0
DSS Export Volume Flow Curves= 0
DXF OffsetX= 0
DXF OffsetY= 0
DXF ScaleX= 0
DXF ScaleY= 0

--- Big Creek.p01 (plan) ---

Plan Title=Floodplain
Program Version=4.00
Geom File=g01
Flow File=f01
K Sum by GR=0
Std Step Tol=0.01
Critical Tol=0.01
Num of Std Step Trials=20
Max Error Tol=0.3
Flow Tol Ratio=0.001
Split Flow NTrial=30
Split Flow Tol=0.02
Split Flow Ratio=0.02
Log Output Level=0
Friction Slope Method=1
Unsteady Friction Slope Method=2
Unsteady Bridges Friction Slope Method=1
Global Log Level=0
CheckData=False
Run HTab=0
Run UNet=0
Run PostProcess=0
UNET Theta=0
UNET Theta Warmup=0
UNET ZTol=0
UNET ZSATol=0
UNET MxIter=0
UNET MaxInSteps=0
UNET DtIC=0
UNET DtMin=0
UNET MaxCRTS=0
UNET WFStab=0
UNET SFStab=0
UNET WFX=0
UNET SFX=0
UNET DSS MLevel=0
UNET DZMax Abort=0
UNET Convert EG Bridges=0
UNET Use Existing IB Tables=0
UNET Froude Limit=0
UNET Froude Power=0
Write IC File=0
Echo Input=False
Echo Output=False
Write Detailed=0

--- Big Creek.f01 (steady flow) ---

Flow Title=NFF Regression Equation
Program Version=4.00
Number of Profiles=1
Profile Names=P100yr
River Rch & RM=Big Creek,Main      ,34457.2
607.0962
River Rch & RM=Big Creek,Main      ,33757.2
647.7837
River Rch & RM=Big Creek,Main      ,31072.5
709.1463
River Rch & RM=Big Creek,Main      ,30746.2
1725.146
River Rch & RM=Big Creek,Main      ,30453.8
1933.517
River Rch & RM=Big Creek,Main      ,26752.8
2006.633
River Rch & RM=Big Creek,Main      ,20980.4
2228.762
River Rch & RM=Big Creek,Main      ,20707.9
2474.321
River Rch & RM=Big Creek,Main      ,13221.2
2650.140
River Rch & RM=Big Creek,Main      ,8167.1
2923.833
River Rch & RM=Big Creek,Main      ,964.7
3246.078
Boundary for River Rch & Prof#=Big Creek,Main      ,1
Up Type=0
Dn Type=3
Dn Slope=0.002936

--- Big Creek.g01 (geometry) ---

Geom Title=USGS 10m DEM
Program Version=4.00

River Reach=Big Creek       ,Main
Reach XY= 30
      1811164.62       90078.585     1808747.535       90619.475
     1806211.141       92274.307      1805574.42       93018.512
     1805580.089        93459.03     1805184.524       93658.867
     1805081.195       94689.366     1803743.364       95822.295
     1802687.024       97968.793     1799345.406       98496.343
     1799158.929       99160.408     1798377.119       99076.856
      1798253.78       99354.369     1798753.104       99478.703
     1798771.008       99728.365     1797799.215      100094.404
     1798054.846      100688.222     1797504.793      101221.365
     1797849.944      101908.682     1796058.543      102449.782
     1795735.275      103162.961     1795068.846      102897.384
     1794888.322      103656.012     1794253.747      103527.202
     1794219.398      104155.642     1793237.169      105005.768
      1793112.33      105712.301     1793478.368       106121.11
     1792413.076      107452.973     1792411.817      107885.955

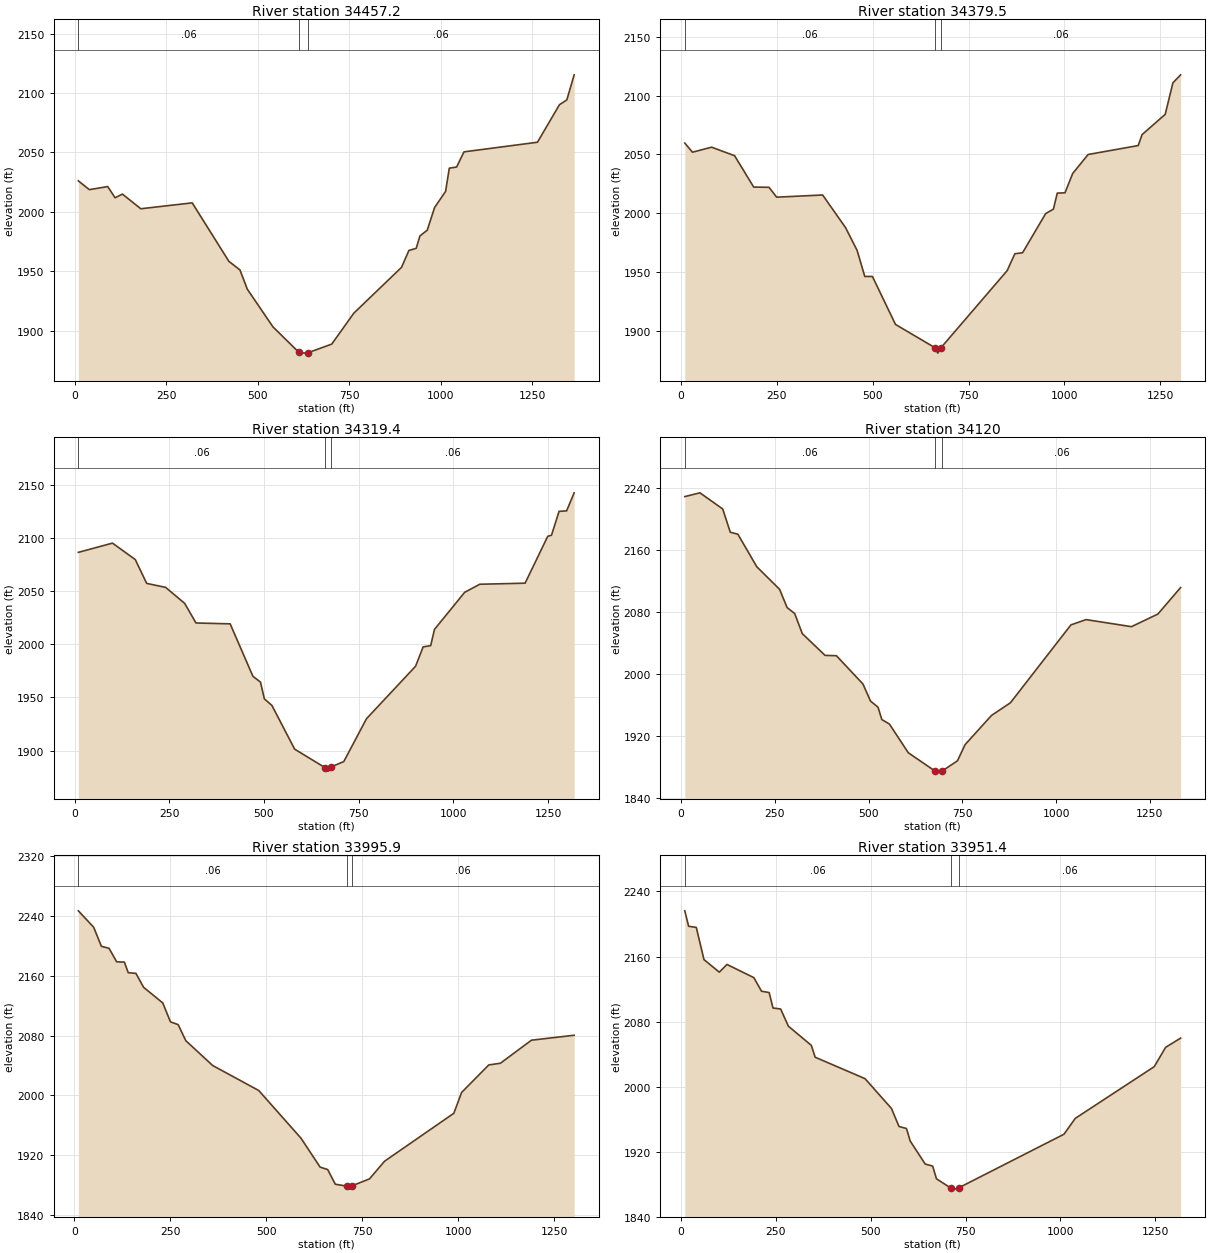
Type RM Length L Ch R = 1 ,34457.2 ,81.1,77.7,74.6
XS GIS Cut Line= 3
     1810854.506       89470.533     1811155.646       90082.998
     1811462.302       90692.763
#Sta/Elev= 30
      10 2026.13    40.1  2018.7    90.3 2021.29   110.4 2011.85   130.5 2014.96
   180.7  2002.6   321.2 2007.56   421.5 1958.28   451.7 1951.05   471.7  1934.9
     542 1903.05   612.2 1881.81   622.3 1880.97   637.3 1881.26   702.6 1888.59
   762.8 1914.62   893.3 1953.26   913.4 1967.48   933.4 1969.27   943.5  1979.7
   963.5 1984.53   983.6 2003.63  1013.7 2017.25  1023.8 2036.77  1043.8 2037.77
  1063.9 2050.53  1264.7 2058.64  1324.9 2090.29    1345  2094.3    1365 2115.43
#Mann= 3 , 0 , 0
      10     .06       0   612.2    .055       0   637.3     .06       0
Bank Sta=612.2,637.3
XS Rating Curve= 0 ,0
Exp/Cntr=0.3,0.1

Type RM Length L Ch R = 1 ,34379.5 ,57.6,60.1,62.6
XS GIS Cut Line= 4
     1810809.673       89506.783     1810997.911       89979.921
     1811165.798       90241.928     1811374.386       90676.909
#Sta/Elev= 30
      10 2059.61      30 2051.86    79.9 2056.11   139.8 2048.87   189.7 2022.14
   229.6 2021.96   249.6 2013.55   369.4 2015.42   429.3 1987.56   459.3 1968.24
   479.3 1946.04   499.2 1946.04   559.4  1905.2  662.83  1885.3  669.68 1880.78
  677.37 1885.17   850.5 1950.99   870.6  1965.4   890.7 1966.23     951 1999.62
   971.1 2003.38   981.2    2017  1001.3 2017.27  1021.4 2033.71  1061.6 2049.88
  1192.2  2057.5  1202.3 2066.81  1262.6 2084.08  1282.7 2110.91  1302.8 2117.72
#Mann= 3 , 0 , 0
      10     .06       0  662.83    .055       0  677.37     .06       0
Bank Sta=662.83,677.37
XS Rating Curve= 0 ,0
Exp/Cntr=0.3,0.1

Type RM Length L Ch R = 1 ,34319.4 ,195.2,199.4,203.6
XS GIS Cut Line= 4
     1810743.648       89527.047     1810971.135       90028.963
     1811130.015       90328.668     1811281.673       90729.478
#Sta/Elev= 30
      10 2086.53   100.2 2095.22   160.3 2079.76   190.4 2057.33   240.5 2053.56
   290.6 2038.55   320.6 2020.05   410.8 2019.23   470.9 1969.85   490.9 1964.38
     501 1948.67     521 1942.45     581 1901.31   660.8 1883.98  670.74 1880.61
   675.8 1884.39   710.7 1889.58   770.6 1929.93   900.2 1979.33   920.2 1997.54
   940.1 1998.74   950.1 2014.01  1029.8 2048.92  1069.7 2056.51  1189.3 2057.51
  1249.1 2101.66    1259 2102.67    1279 2125.12  1298.9 2125.57  1318.8 2142.56
#Mann= 3 , 0 , 0
      10     .06       0   660.8    .055       0   675.8     .06       0
Bank Sta=660.8,675.8
XS Rating Curve= 0 ,0
Exp/Cntr=0.3,0.1

Type RM Length L Ch R = 1 ,34120   ,122.4,124.1,125.7
XS GIS Cut Line= 3
     1810573.176       89600.514     1810777.007       90018.366
     1811072.561       90833.688
#Sta/Elev= 30
    10.1 2229.13    50.5 2233.98   111.2 2213.13   131.4 2183.13   151.6 2180.55
   202.1 2138.53   262.8 2109.45     283 2085.83   303.2  2078.1   323.4 2052.21
   384.1 2024.16   414.4  2023.7   485.1 1987.23   505.3 1965.17   525.4 1957.21
   535.5 1941.26   555.7 1935.51   606.1 1898.41   676.7 1875.04   686.8 1874.71
   696.9 1875.04   737.2 1888.08   757.4 1908.87   827.9 1946.57   878.4 1962.97
  1039.7 2063.49  1080.1 2070.32  1201.1  2061.2  1271.6 2077.49  1332.2 2111.72
#Mann= 3 , 0 , 0
    10.1     .06       0   676.7    .055       0   696.9     .06       0
Bank Sta=676.7,696.9
XS Rating Curve= 0 ,0
Exp/Cntr=0.3,0.1

Type RM Length L Ch R = 1 ,33995.9 ,40.4,44.6,48.7
XS GIS Cut Line= 4
     1810520.933       89616.486     1810720.642       90213.946
     1810791.867       90450.515     1810982.434       90829.975
#Sta/Elev= 30
      10 2246.92      50 2224.96      70 2199.48      90 2196.74     110 2178.63
     130 2178.31     140 2164.14     160 2163.21     180 2144.57     230 2123.62
     250 2098.32     270 2094.65     290 2073.11     360 2039.89     480 2006.43
     590 1942.63   639.8 1903.92   659.6 1900.63   679.4 1880.99     709 1878.51
  715.95 1874.44     724 1879.14   768.3 1888.08   807.8 1911.82   988.2 1975.98
  1008.4 2003.84  1079.2 2040.66  1109.5 2042.94  1190.4 2073.78  1301.6 2080.38
#Mann= 3 , 0 , 0
      10     .06       0     709    .055       0     724     .06       0
Bank Sta=709,724
XS Rating Curve= 0 ,0
Exp/Cntr=0.3,0.1

Type RM Length L Ch R = 1 ,33951.4 ,192.8,194.1,195.4
XS GIS Cut Line= 4
     1810447.554       89631.764     1810667.819        90097.57
     1810729.204       90487.547     1810866.419       90870.303
#Sta/Elev= 30
    10.1 2216.18    20.2 2197.21    40.4 2195.78    60.6 2156.25     101 2140.76
   121.2 2150.26     192 2134.04   212.2 2117.35   232.4 2115.68   242.5  2096.7
   262.7 2095.45   282.9 2074.42   343.5 2050.74   353.6 2036.18     485  2009.8
   554.7 1973.14   574.5 1951.02   594.2 1948.52   604.1 1933.06   643.6 1904.81
   663.3 1902.29   673.2  1886.7   712.6 1874.83   722.5 1873.96   732.4 1875.68
  1009.2 1941.46    1039 1960.98  1247.2 2024.61    1277 2048.29  1316.6 2059.67
#Mann= 3 , 0 , 0
    10.1     .06       0   712.6    .045       0   732.4     .06       0
Bank Sta=712.6,732.4
XS Rating Curve= 0 ,0
Exp/Cntr=0.3,0.1

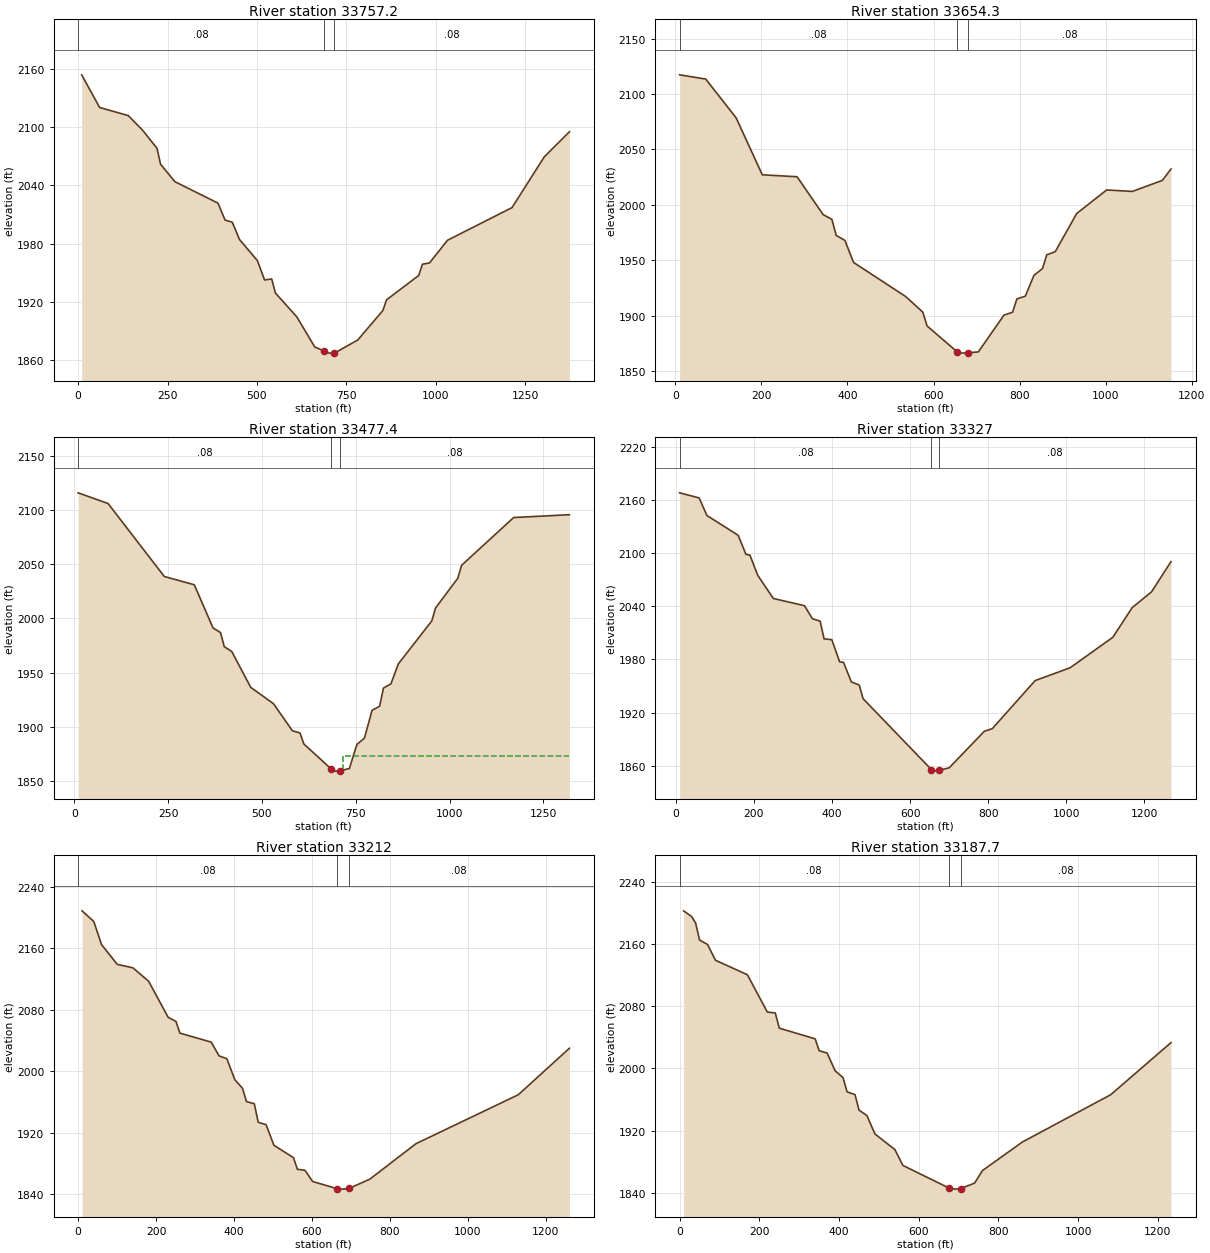
Type RM Length L Ch R = 1 ,33757.2 ,106.8,102.9,99
XS GIS Cut Line= 3
     1810288.674       89635.375     1810490.885       90180.621
     1810581.157       90967.798
#Sta/Elev= 30
      10 2154.05    60.2 2120.37   140.4 2112.01   180.5 2096.87   220.6 2078.31
   230.6 2061.85   270.7 2043.88     391 2021.79   411.1 2004.26   431.1 2002.13
   451.2 1984.34   501.3 1962.53   521.4 1942.54   541.4 1943.58   551.5 1929.19
   611.6 1904.49   661.8 1873.44   686.9 1869.61   701.9 1867.12   716.9 1867.13
   782.1 1880.71   852.3  1911.1   862.4 1922.04   952.6 1947.24   962.7 1958.77
   982.7 1960.11  1032.9 1983.49  1213.4 2017.18  1303.7 2069.57  1373.9 2095.39
#Mann= 3 , 0 , 0
       0     .08       0   686.9    .045       0   716.9     .08       0
Bank Sta=686.9,716.9
XS Rating Curve= 0 ,0
Exp/Cntr=0.3,0.1

Type RM Length L Ch R = 1 ,33654.3 ,178.9,176.9,175
XS GIS Cut Line= 4
     1810201.529       89700.822     1810369.906       90198.633
     1810461.415       90564.671     1810534.623       90802.595
#Sta/Elev= 30
    10.1 2117.28    70.7 2113.47   141.5 2078.43   202.1 2027.16     283  2025.4
   343.6 1991.24   363.8 1987.05   373.9 1972.49   394.1 1968.02   414.3 1948.12
   535.4  1917.4   575.2 1903.29   585.1 1890.89   654.6 1867.66   664.5 1866.39
   679.5 1866.59   704.2 1867.53   763.8 1900.68   783.7 1903.22   793.6 1915.19
   813.5 1917.78   833.3 1936.49   853.2 1942.58   863.1 1954.95     883 1957.91
   932.7 1992.25  1002.4  2013.5  1062.1 2012.16  1131.8 2022.13  1151.8 2032.39
#Mann= 3 , 0 , 0
    10.1     .08       0   654.6    .045       0   679.5     .08       0
Bank Sta=654.6,679.5
XS Rating Curve= 0 ,0
Exp/Cntr=0.3,0.1

Type RM Length L Ch R = 1 ,33477.4 ,144.6,150.4,156.2
XS GIS Cut Line= 4
     1810137.016       89722.036     1810158.682       90140.901
     1810277.842       90527.267     1810400.612       91007.517
#Sta/Elev= 30
      10 2115.88    89.9 2106.01   239.7  2038.7   319.6 2031.08   369.5 1991.31
   389.5 1986.96   399.5 1973.96   419.4 1969.55     470 1936.47   530.6 1921.38
   581.2 1896.33   601.4 1894.37   611.5 1884.25   685.1 1860.94   692.3 1859.16
   707.3 1859.45   732.8 1861.53     753 1883.78   773.2 1889.67   793.4 1915.26
   813.6 1919.04   823.7 1935.75   843.6 1939.64   863.4 1958.07   952.6 1997.75
   962.5  2009.6    1022 2037.16  1031.9    2049  1170.7 2093.08  1319.4 2095.68
#Mann= 3 , 0 , 0
      10     .08       0   685.1    .045       0   707.3     .08       0
#XS Ineff= 2 , 0
                          716.68         1873.29
Permanent Ineff=
       F       F
Bank Sta=685.1,707.3
XS Rating Curve= 0 ,0
Exp/Cntr=0.3,0.1

Type RM Length L Ch R = 1 ,33327   ,114.6,115,115.3
XS GIS Cut Line= 4
     1809996.548       89748.406     1810069.755       90242.557
      1810117.34       90630.557     1810208.849       90996.595
#Sta/Elev= 30
      10 2168.11    59.9 2162.35    79.9 2142.48   159.9 2120.14   179.8 2098.57
   189.8  2097.9   209.8 2075.14   249.8 2048.81   329.7 2040.67   349.7 2026.01
   369.7 2023.19   379.7 2003.27   399.6  2002.3   419.6  1977.3   429.6 1976.63
   449.6 1954.57   469.6 1951.18   479.6 1935.66  654.49 1855.64   659.9 1853.88
   674.9 1854.87     700 1857.62   790.2 1898.94   810.3  1901.8   920.2 1956.15
  1009.6 1970.58  1118.8 2004.94  1168.5 2038.47  1218.1 2056.32  1267.8 2090.41
#Mann= 3 , 0 , 0
      10     .08       0  654.49    .045       0   674.9     .08       0
Bank Sta=654.49,674.9
XS Rating Curve= 0 ,0
Exp/Cntr=0.3,0.1

Type RM Length L Ch R = 1 ,33212   ,23.6,24.3,25.1
XS GIS Cut Line= 4
     1809942.253       89763.702     1809970.235       90325.871
      1810000.76       90598.053     1810064.354       91017.772
#Sta/Elev= 30
    10.1 2208.42    40.2 2194.61    60.3  2164.4   100.5 2138.84   140.7 2134.31
   180.9 2116.95   231.2 2069.98   251.3 2064.57   261.3 2049.42   341.7 2037.72
   361.8 2019.89   381.9 2016.11     402 1989.14   422.1 1977.63   432.2 1960.37
   452.3 1957.62   462.4 1933.46   482.5 1930.42   502.6 1903.65   552.8 1887.49
   562.9 1872.38   582.4 1871.08     602  1856.5   665.2 1847.11   680.2 1846.59
   695.2 1847.44   748.7  1859.5   867.1  1905.6  1129.9 1969.27  1261.3 2029.77
#Mann= 3 , 0 , 0
       0     .08       0   665.2    .045       0   695.2     .08       0
Bank Sta=665.2,695.2
XS Rating Curve= 0 ,0
Exp/Cntr=0.3,0.1

Type RM Length L Ch R = 1 ,33187.7 ,29.5,30.4,31.3
XS GIS Cut Line= 4
     1809932.488       89772.833      1809956.37       90402.698
     1809977.266        90641.51     1810016.072       91002.712
#Sta/Elev= 30
      10 2202.58      30 2195.29      40 2187.05      50 2165.03      70 2159.33
      90 2139.04   170.1 2120.38   220.1 2072.45   240.1 2071.29   250.1 2051.75
   340.2 2037.98   350.2 2022.75   370.2 2019.76   390.2 1997.05   410.2 1988.08
   420.2 1969.93   440.2 1966.32   450.2 1946.45   470.2 1939.24   490.2 1915.73
   540.3 1895.61   560.3  1875.3   675.2 1846.42   690.2  1844.8   705.2 1845.51
   740.2  1852.5   760.2 1868.68   860.1 1905.31    1082 1966.16  1233.3 2033.15
#Mann= 3 , 0 , 0
       0     .08       0   675.2    .045       0   705.2     .08       0
Bank Sta=675.2,705.2
XS Rating Curve= 0 ,0
Exp/Cntr=0.3,0.1

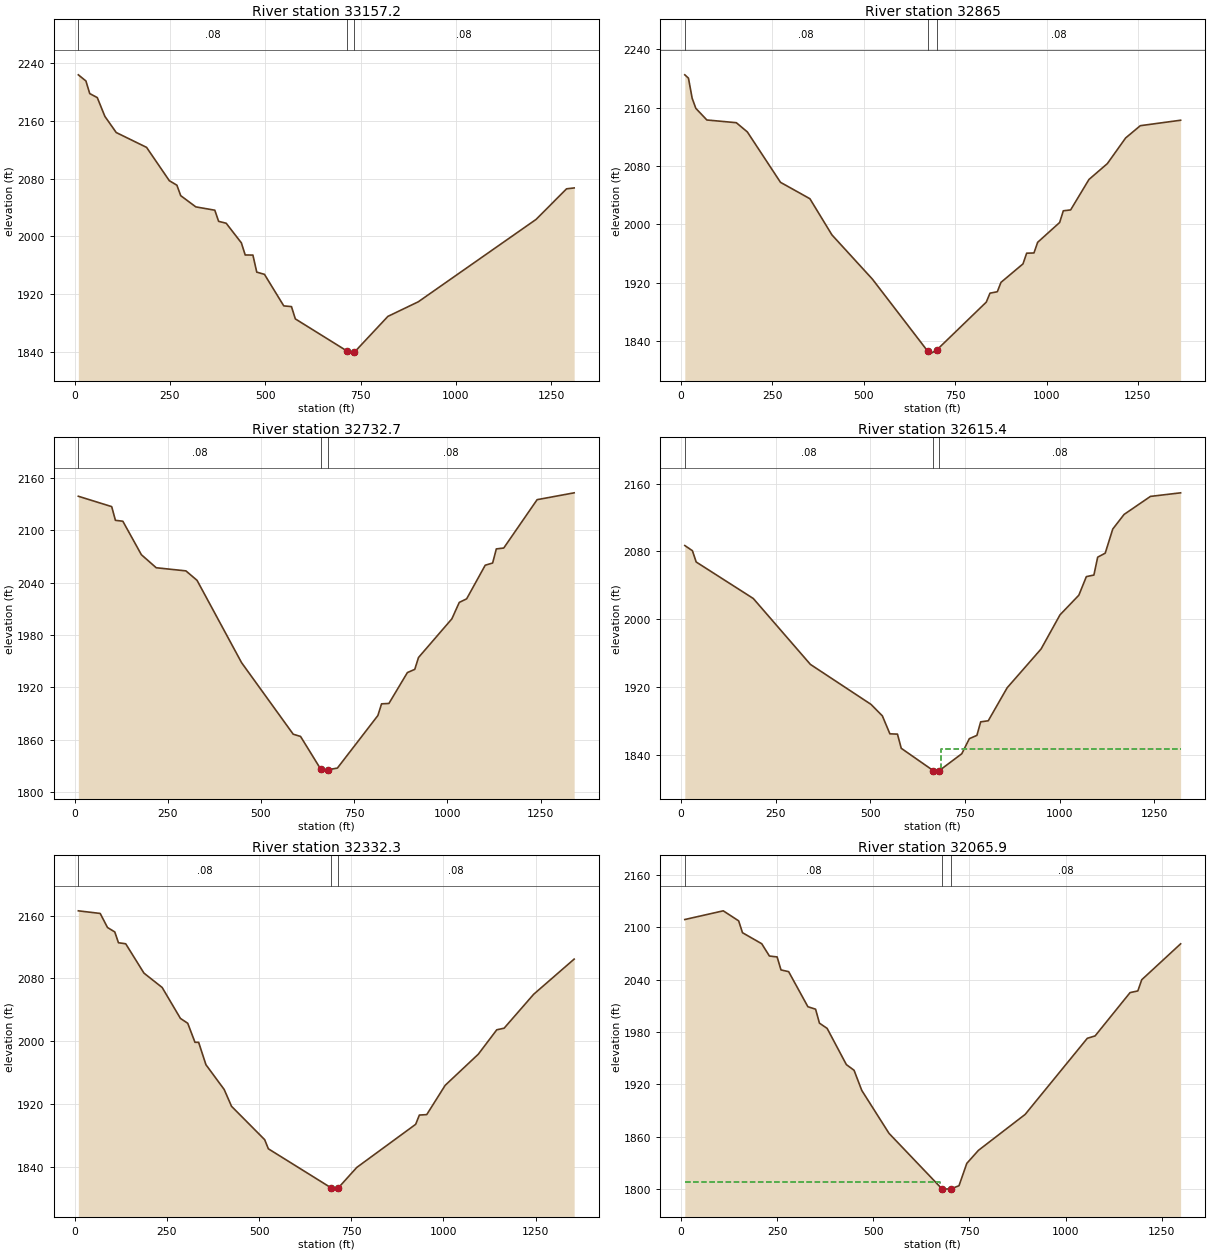
Type RM Length L Ch R = 1 ,33157.2 ,291,292.3,291.4
XS GIS Cut Line= 4
     1809898.697       89747.312     1809916.751       90184.232
     1809938.417        90577.82     1809978.137       91054.459
#Sta/Elev= 30
     9.9 2224.14    29.8 2215.63    39.8 2198.12    59.6 2192.51    79.5 2166.47
   109.3 2144.02   188.8 2123.44   248.5 2077.14   268.3 2070.92   278.3 2056.42
     318 2040.79   367.7 2036.22   377.7 2020.75   397.5 2018.12   437.3 1990.91
   447.4 1974.06   467.6  1973.9   477.7 1950.23   497.9 1947.16   548.5  1903.4
   568.7 1902.37   578.8 1885.32   715.4 1840.36   730.4  1837.8  733.73 1839.14
   821.4 1888.77   901.2 1909.08  1210.1 2023.48  1289.8 2065.87  1309.8 2067.12
#Mann= 3 , 0 , 0
     9.9     .08       0   715.4    .045       0  733.73     .08       0
Bank Sta=715.4,733.73
XS Rating Curve= 0 ,0
Exp/Cntr=0.3,0.1

Type RM Length L Ch R = 1 ,32865   ,136.5,132.3,130.1
XS GIS Cut Line= 3
     1809638.836       89755.979     1809645.951       90440.616
     1809700.628        91120.54
#Sta/Elev= 30
    10.1 2204.76    20.1 2200.22    30.2  2172.8    40.3 2158.88    70.5 2142.97
     151 2139.27   181.2 2126.67   271.9  2057.7   352.4 2035.25   412.8  1985.7
   523.6 1925.13   674.6 1826.77   684.7 1823.98   699.7 1828.35   835.1  1893.8
   845.2 1906.02   865.2 1907.96   875.3  1920.8   935.5 1946.11   945.5  1960.7
   965.5 1961.04   975.6 1975.59  1035.8 2002.72  1045.8  2018.7  1065.9 2019.95
    1116 2061.59  1166.2 2083.22  1216.3 2118.36  1256.5 2135.17  1366.8 2142.64
#Mann= 3 , 0 , 0
    10.1     .08       0   674.6    .045       0   699.7     .08       0
Bank Sta=674.6,699.7
XS Rating Curve= 0 ,0
Exp/Cntr=0.3,0.1

Type RM Length L Ch R = 1 ,32732.7 ,119.8,117.3,114.9
XS GIS Cut Line= 4
     1809458.472        89781.35     1809487.755        90268.18
     1809546.321       90648.859     1809641.491       91106.406
#Sta/Elev= 30
      10 2138.95    99.5 2127.07   109.5 2111.38   129.4 2110.32   179.2 2071.93
     219    2057   298.6 2053.42   328.5 2042.58   447.9 1948.26   586.5 1866.21
   606.2 1863.65   660.1 1826.29  673.86  1823.9   680.5 1825.56     705 1827.38
   813.6 1887.62   823.5 1901.03   843.2 1901.45   892.8 1936.86   912.6 1940.55
   922.6 1954.12  1012.1 1998.43    1032 2017.28  1051.8 2021.39  1101.6  2059.9
  1121.5 2062.43  1131.4 2078.59  1151.3 2079.61  1240.8 2135.03  1340.2 2142.88
#Mann= 3 , 0 , 0
      10     .08       0   660.1    .045       0   680.5     .08       0
Bank Sta=660.1,680.5
XS Rating Curve= 0 ,0
Exp/Cntr=0.3,0.1

Type RM Length L Ch R = 1 ,32615.4 ,281.4,283.1,284.9
XS GIS Cut Line= 4
     1809346.229        89819.53     1809335.396       90191.454
     1809447.334       90668.093     1809544.828       91115.845
#Sta/Elev= 30
    10.1    2087    30.2 2080.89    40.2 2067.54   191.1 2024.39   341.9 1946.52
     502 1899.28     532  1885.7   551.9 1864.48   571.9 1864.14   581.9 1847.38
   666.8 1820.91  671.75  1820.4   681.8 1820.83   741.8 1840.96   761.8 1858.78
   781.8 1862.66   791.7 1878.62   811.7  1879.9   861.7 1918.93   951.3 1964.76
  1001.2 2005.03    1051 2028.28  1070.9 2050.26  1090.8 2052.12  1100.8 2073.23
  1120.7 2077.96  1140.6 2106.47  1170.5 2123.73  1240.2 2145.05  1319.9 2149.28
#Mann= 3 , 0 , 0
    10.1     .08       0   666.8    .045       0   681.8     .08       0
#XS Ineff= 2 , 0
                          687.96          1846.7
Permanent Ineff=
       F       F
Bank Sta=666.8,681.8
XS Rating Curve= 0 ,0
Exp/Cntr=0.3,0.1

Type RM Length L Ch R = 1 ,32332.3 ,265.4,266.4,267.4
XS GIS Cut Line= 4
     1809050.135       89844.807     1809079.022       90249.228
     1809165.684       90751.143     1809259.567       91180.841
#Sta/Elev= 30
     9.9 2166.27    69.2 2162.93      89 2145.01   108.8  2139.3   118.7 2125.56
   138.4 2124.22   187.9 2086.79   237.3 2068.44   286.8 2028.99   306.6 2022.81
   326.3 1998.47   336.2 1998.47     356 1969.89   405.5 1938.29   425.4 1916.84
   515.3 1874.25   525.3 1862.63   695.1 1812.91   705.1 1811.17   715.1 1812.84
     765 1838.84   924.8 1893.88   934.8 1905.67   954.8 1906.26  1004.8 1943.61
  1094.7 1983.37  1144.7 2014.46  1164.7 2016.53  1244.7 2059.75  1354.6 2104.67
#Mann= 3 , 0 , 0
     9.9     .08       0   695.1    .045       0   715.1     .08       0
Bank Sta=695.1,715.1
XS Rating Curve= 0 ,0
Exp/Cntr=0.3,0.1

Type RM Length L Ch R = 1 ,32065.9 ,468.4,454.7,441
XS GIS Cut Line= 4
     1808788.344       89906.278     1808851.535       90371.999
     1808905.699       90772.809     1809064.578       91166.397
#Sta/Elev= 30
      10 2108.63     110 2118.58     150 2107.12     160 2093.54     210 2080.95
     230 2066.88     250 2065.86     260 2051.02     280 2048.99     330 2008.89
     350  2006.1     360 1990.13     380 1984.14     430 1942.72     450 1936.25
     470 1913.25   540.8 1864.13  679.11 1800.36   682.3 1800.31   702.5  1800.7
   722.8 1804.22     743 1829.72   773.3 1844.64   894.7 1885.73  1056.3 1972.78
  1076.6 1975.54  1167.5 2025.06  1187.7 2026.98  1197.8 2039.75  1298.9 2080.83
#Mann= 3 , 0 , 0
      10     .08       0  679.11    .045       0   702.5     .08       0
#XS Ineff= 2 , 0
          672.39 1808.79
Permanent Ineff=
       F       F
Bank Sta=679.11,702.5
XS Rating Curve= 0 ,0
Exp/Cntr=0.3,0.1

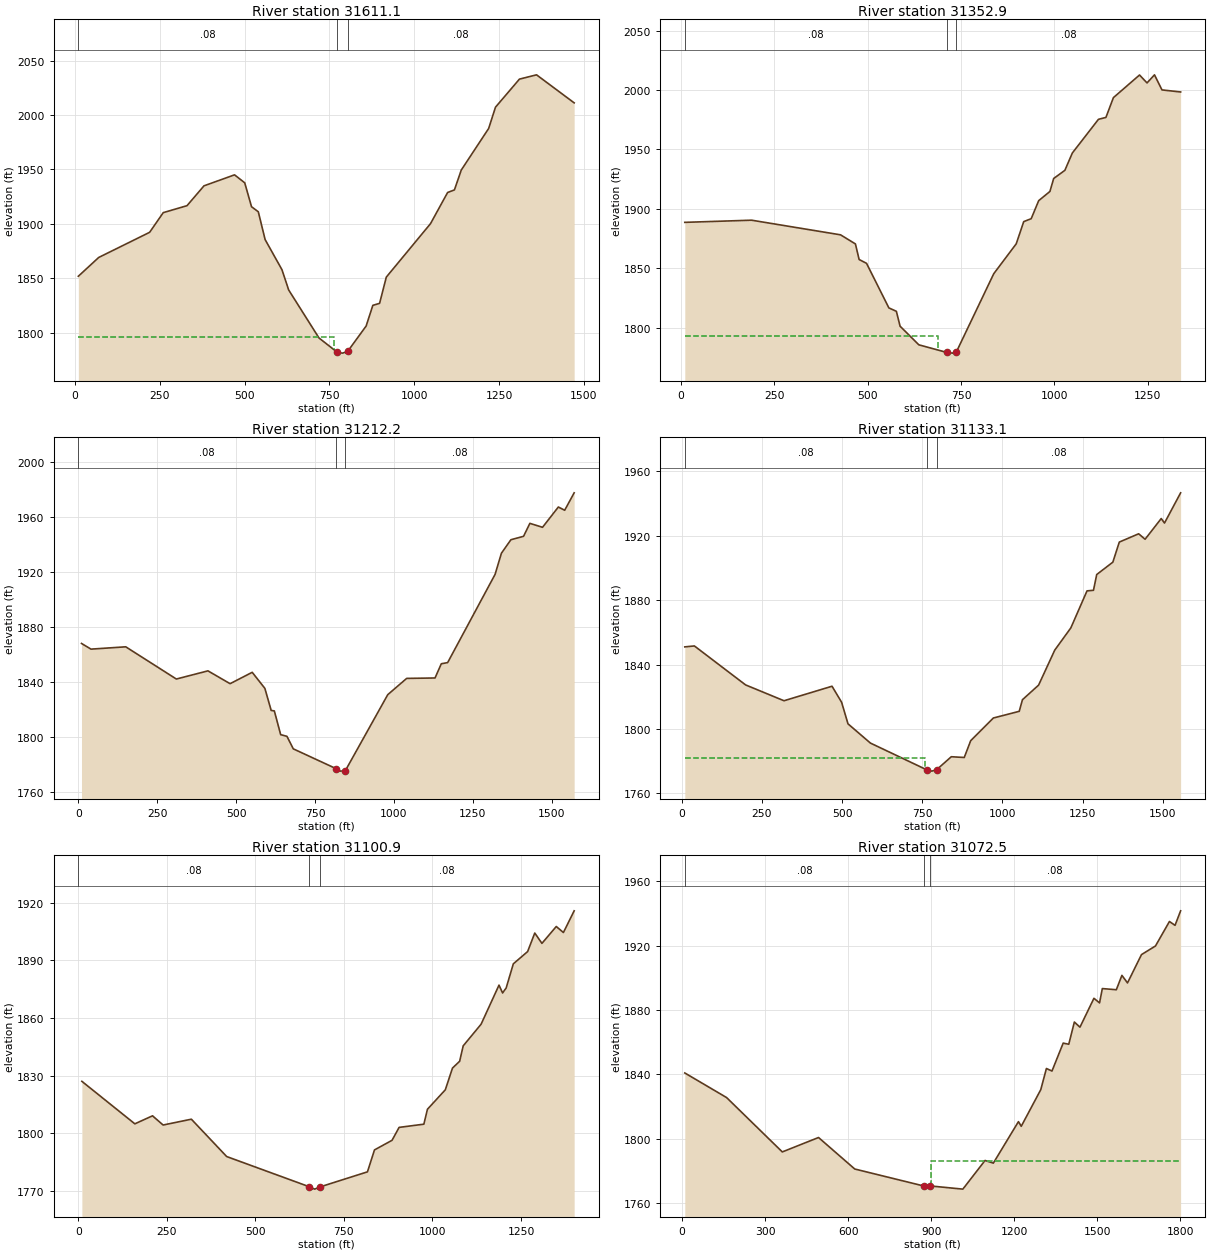
Type RM Length L Ch R = 1 ,31611.1 ,259,258.3,257.6
XS GIS Cut Line= 4
     1808196.608        90037.99     1808341.044       90579.625
     1808566.725       90918.148     1808711.161       91401.106
#Sta/Elev= 30
      10 1851.75    70.1 1869.02   220.2 1892.13   260.3  1910.2   330.3  1916.6
   380.4 1934.83   470.5 1944.94   500.5 1937.59   520.5 1915.67   540.5 1910.98
   560.6 1885.44   610.2 1857.79     630 1839.16   719.3 1795.06   773.8 1781.76
   788.8 1781.11   803.8 1782.67   858.3 1805.98   878.1 1825.01     898 1826.86
   917.8 1850.96  1048.1 1900.08  1098.5 1928.71  1118.6  1931.1  1138.8 1949.36
  1219.5 1987.55  1239.6 2007.08  1310.2 2032.89  1360.6 2036.84  1471.5 2011.09
#Mann= 3 , 0 , 0
      10     .08       0   773.8    .045       0   803.8     .08       0
#XS Ineff= 2 , 0
          762.45 1795.88
Permanent Ineff=
       F       F
Bank Sta=773.8,803.8
XS Rating Curve= 0 ,0
Exp/Cntr=0.3,0.1

Type RM Length L Ch R = 1 ,31352.9 ,136.9,140.6,143.8
XS GIS Cut Line= 4
     1808235.906        90264.52     1808188.321       90798.935
     1808433.566       91153.991     1808697.113       91413.878
#Sta/Elev= 30
     9.9 1888.66   188.8 1890.48   427.2 1878.16     467  1870.5   476.9  1857.4
   496.8 1854.17   556.6 1816.67   576.7 1813.79   586.7 1801.25   636.9 1785.59
   712.2 1779.15   727.2  1778.6   737.2 1779.45   837.6 1845.44   897.8  1870.6
   917.9 1889.28   937.9 1891.74     958 1906.93   988.1 1914.67   998.1 1925.57
  1028.1 1932.44  1048.1 1947.01  1118.1 1975.38  1138.1 1976.98  1158.1 1993.61
  1228.1 2012.67  1248.2    2006  1268.2 2012.82  1288.2 2000.13  1338.2 1998.38
#Mann= 3 , 0 , 0
     9.9     .08       0   712.2    .045       0   737.2     .08       0
#XS Ineff= 2 , 0
          687.81 1793.17
Permanent Ineff=
       F       F
Bank Sta=712.2,737.2
XS Rating Curve= 0 ,0
Exp/Cntr=0.3,0.1

Type RM Length L Ch R = 1 ,31212.2 ,78.3,79.1,80.6
XS GIS Cut Line= 4
     1808210.283       90216.935     1808089.491        90846.52
     1808327.415       91307.727     1808693.453       91494.406
#Sta/Elev= 30
      10 1868.06    40.1 1863.94   150.3 1865.62   310.5 1842.25   410.7 1848.18
   480.8 1838.87   550.9 1847.12     591 1835.48     611 1819.46     621 1819.13
   641.1 1801.89     661 1800.68     681 1791.61   815.7 1777.34   830.7 1775.44
   845.7 1775.65   980.4 1830.93  1040.3 1842.71  1130.1 1843.01    1150 1853.33
  1170.1 1854.17  1320.4 1918.18  1340.4  1933.5  1370.5  1943.3  1410.6 1945.79
  1430.6 1955.19  1470.7 1952.32  1520.8 1967.03  1540.9 1964.69  1570.9 1977.33
#Mann= 3 , 0 , 0
       0     .08       0   815.7    .045       0   845.7     .08       0
Bank Sta=815.7,845.7
XS Rating Curve= 0 ,0
Exp/Cntr=0.3,0.1

Type RM Length L Ch R = 1 ,31133.1 ,34.3,32.2,30.1
XS GIS Cut Line= 4
     1808171.484       90309.337     1808022.039       90878.502
     1808219.179       91275.963     1808648.438       91574.854
#Sta/Elev= 30
      10 1850.96    39.9 1851.54   199.5 1827.31   319.2 1817.47   468.8 1826.49
   498.7 1816.53   518.6 1803.12   588.5 1791.15     765 1774.44     780 1773.71
     795 1774.62   840.5 1782.66   880.9 1782.19     901 1792.63   971.6 1806.74
  1052.2 1810.89  1062.3 1818.11  1112.6 1827.18  1162.9 1848.93  1213.2 1862.81
  1263.5 1885.78  1283.6 1886.14  1293.7 1895.93    1344 1903.64  1364.1 1916.12
  1424.4 1921.27  1444.5 1917.88  1494.8 1930.76  1504.9 1927.94  1555.2 1946.74
#Mann= 3 , 0 , 0
      10     .08       0     765    .045       0     795     .08       0
#XS Ineff= 2 , 0
           759.8 1781.83
Permanent Ineff=
       F       F
Bank Sta=765,795
XS Rating Curve= 0 ,0
Exp/Cntr=0.3,0.1

Type RM Length L Ch R = 1 ,31100.9 ,29.1,28.5,27.9
XS GIS Cut Line= 4
     1808113.459       90436.579     1807974.758       90884.385
     1808220.457       91304.451     1808577.117       91569.965
#Sta/Elev= 30
      10 1827.06   159.6 1804.96   209.5 1809.13   239.4 1804.34   319.2 1807.37
   418.9 1787.95   652.4 1772.23   667.4 1771.01   682.4 1772.16   816.4 1779.99
   836.3  1791.4   885.9  1796.4   905.8 1803.11   975.7 1804.78   985.8 1812.53
  1036.3 1822.66  1056.5 1833.94  1076.7 1837.48  1086.8 1845.51  1137.3 1856.75
  1187.9 1877.08    1198 1873.01  1208.1 1875.59  1228.3 1888.14  1268.7 1894.52
  1288.9 1904.16  1309.1 1898.79  1349.6 1907.56  1369.8 1904.43  1400.1 1915.71
#Mann= 3 , 0 , 0
       0     .08       0   652.4    .045       0   682.4     .08       0
Bank Sta=652.4,682.4
XS Rating Curve= 0 ,0
Exp/Cntr=0.3,0.1

Type RM Length L Ch R = 1 ,31072.5 ,12.8,12.3,12
XS GIS Cut Line= 4
     1808153.316       90255.962     1807944.377       90896.876
     1808190.033       91297.761       1808709.1       91699.474
#Sta/Elev= 30
    10.1 1840.84     161 1825.56   362.2 1791.78     493 1800.74   623.8 1781.17
   874.2 1770.57   894.2 1770.69  1014.2 1768.67  1094.3 1786.47  1124.3 1784.82
    1215 1810.62  1225.1 1807.72  1295.7 1830.51  1315.9 1843.61  1336.1 1842.04
  1376.5 1859.38  1396.7 1858.68  1416.9 1872.48  1437.1 1869.29  1487.6 1887.23
  1507.8 1884.37  1517.9 1893.27  1568.4 1892.54  1588.6 1901.47  1608.8 1896.77
  1659.3 1914.38  1709.8 1919.73  1760.2 1934.95  1780.4 1932.55  1800.6 1941.57
#Mann= 3 , 0 , 0
    10.1     .08       0   874.2    .045       0   894.2     .08       0
#XS Ineff= 2 , 0
                          899.44         1786.22
Permanent Ineff=
       F       F
Bank Sta=874.2,894.2
XS Rating Curve= 0 ,0
Exp/Cntr=0.3,0.1

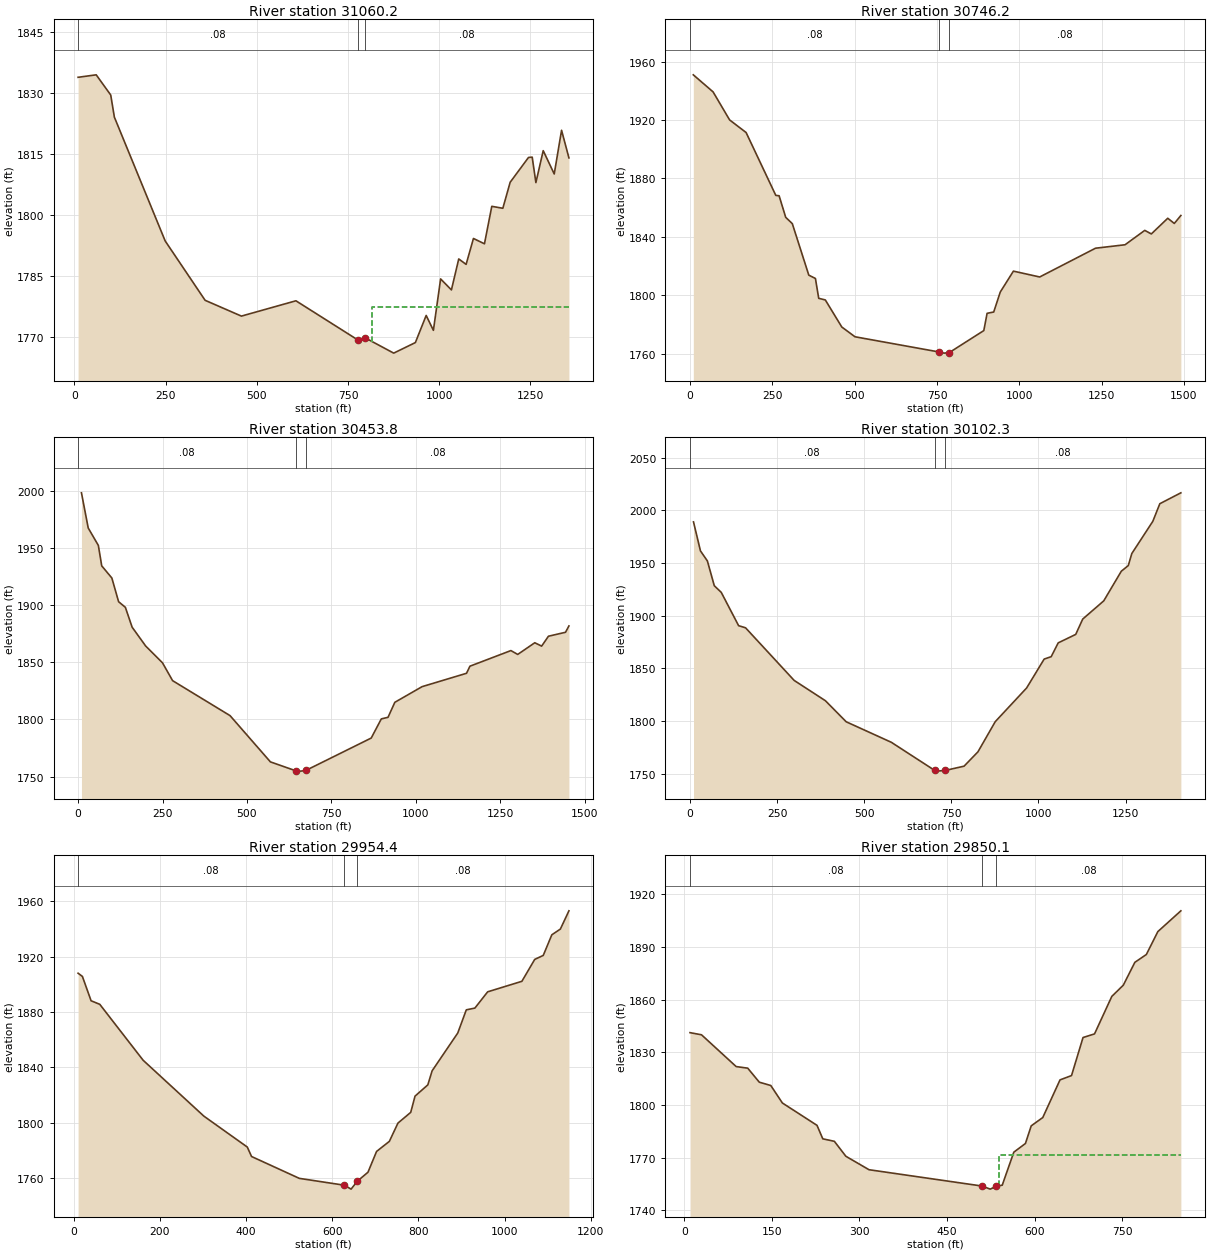
Type RM Length L Ch R = 1 ,31060.2 ,295.4,314,332.3
XS GIS Cut Line= 5
     1807913.096       90328.197     1807937.335       90914.905
     1807996.516       91007.975     1808176.864       91291.599
     1808370.366       91549.169
#Sta/Elev= 30
      10 1833.93    59.7 1834.54    99.5 1829.57   109.5 1824.12   248.8 1793.62
   358.3    1779   457.8 1775.11   607.3 1778.88   776.6 1769.26   796.4 1769.79
   875.4 1765.99   934.8 1768.59   964.4 1775.27   984.2  1771.6    1004 1784.27
  1033.6 1781.56  1053.7 1789.19  1073.9 1787.85    1094 1794.23  1124.2 1792.92
  1144.3 1802.15  1174.6 1801.67  1194.7 1808.08    1245 1814.19  1255.1 1814.26
  1265.2 1807.99  1285.3 1815.86  1315.5 1810.12  1335.6 1820.88  1355.8 1814.08
#Mann= 3 , 0 , 0
      10     .08       0   776.6    .045       0   796.4     .08       0
#XS Ineff= 2 , 0
                          816.75         1777.31
Permanent Ineff=
       F       F
Bank Sta=776.6,796.4
XS Rating Curve= 0 ,0
Exp/Cntr=0.3,0.1

Type RM Length L Ch R = 1 ,30746.2 ,320.6,292.4,264
XS GIS Cut Line= 4
     1807650.459       90430.676     1807781.354       91017.447
     1807763.299       91337.915     1807984.467       91861.496
#Sta/Elev= 30
      10 1950.88    70.1 1939.18   120.2 1920.02   170.3 1911.39   260.5 1868.36
   270.5  1868.1   290.6 1853.32   310.6 1849.03   360.7 1813.76   380.8 1811.48
   390.8  1797.9   410.8  1796.8   460.9 1778.26     501 1771.58   756.7 1761.16
   771.7 1760.39   786.7 1760.68   892.1 1775.82   902.1 1787.63   922.2 1788.54
   942.1  1802.2     982 1816.51  1061.8 1812.51  1231.3  1832.2    1321 1834.56
  1380.9 1844.41  1400.8 1841.97  1450.7  1852.7  1470.6 1849.15  1490.5  1854.6
#Mann= 3 , 0 , 0
       0     .08       0   756.7    .045       0   786.7     .08       0
Bank Sta=756.7,786.7
XS Rating Curve= 0 ,0
Exp/Cntr=0.3,0.1

Type RM Length L Ch R = 1 ,30453.8 ,351.4,351.5,350.8
XS GIS Cut Line= 4
     1807096.543       90721.176     1807357.073       91112.234
     1807704.622       91410.133      1807933.08       91883.581
#Sta/Elev= 30
      10  1998.2      30 1967.45      60  1952.2      70 1934.33     100 1923.68
     120 1902.94     140 1898.05     160 1880.69     200 1864.24   249.9 1849.52
   279.9 1833.89   449.9 1803.32   569.4 1762.86     644 1755.11     659 1754.76
     674 1755.31   867.9 1783.69   897.8 1800.44   917.7 1801.84   937.8 1814.95
  1018.6 1828.66  1150.1 1840.35  1160.2 1846.55  1281.5 1860.21  1301.7 1856.84
  1352.2 1867.06  1372.5 1864.11  1392.7 1872.77  1443.2 1876.22  1453.3 1881.75
#Mann= 3 , 0 , 0
       0     .08       0     644    .045       0     674     .08       0
Bank Sta=644,674
XS Rating Curve= 0 ,0
Exp/Cntr=0.3,0.1

Type RM Length L Ch R = 1 ,30102.3 ,146.4,147.9,149.4
XS GIS Cut Line= 4
     1806942.383       90860.599     1807207.559       91374.024
     1807455.808       91588.421      1807653.28       92051.068
#Sta/Elev= 30
      10 1989.01    29.9 1961.51    49.8 1951.95    69.7 1928.39    89.7 1922.06
   139.5 1890.46   159.4 1888.45   298.9 1838.49   388.6 1819.22   448.3 1799.21
   577.9 1779.72     702 1753.11   707.1 1752.36     732 1752.97   786.6 1757.06
   826.4 1770.66   876.1 1799.32   966.2 1831.33  1016.5 1858.75  1036.7 1861.03
  1056.8 1874.14  1107.1 1882.18  1127.2 1896.74  1187.6 1914.05  1237.9 1942.15
    1258 1947.56  1268.1 1958.97  1328.4 1989.55  1348.5 2006.27  1408.9 2016.61
#Mann= 3 , 0 , 0
       0     .08       0     702    .045       0     732     .08       0
Bank Sta=702,732
XS Rating Curve= 0 ,0
Exp/Cntr=0.3,0.1

Type RM Length L Ch R = 1 ,29954.4 ,85,104.3,123.6
XS GIS Cut Line= 4
     1806932.097       91015.065     1807178.314       91533.522
     1807302.423       91647.622     1807512.608       91995.929
#Sta/Elev= 30
    10.1 1907.96    20.1 1905.64    40.3 1888.07    60.4 1885.54   161.1 1845.17
   302.1 1804.85   402.8 1782.57   412.8 1775.73   523.6 1759.97   628.4 1755.02
  643.74 1752.21   658.4 1757.95     683 1764.41   702.9 1779.39   732.6 1786.66
   752.5 1799.83   782.2 1807.59   792.2 1819.29   821.9 1827.42   831.8 1837.52
   891.4 1864.84   911.2 1881.54   931.1  1882.8   960.8 1894.53  1040.2 1902.12
    1070 1917.92  1089.8 1920.79  1109.7 1935.67  1129.5  1939.8  1149.4 1952.96
#Mann= 3 , 0 , 0
    10.1     .08       0   628.4    .045       0   658.4     .08       0
Bank Sta=628.4,658.4
XS Rating Curve= 0 ,0
Exp/Cntr=0.3,0.1

Type RM Length L Ch R = 1 ,29850.1 ,132.9,138.5,144.1
XS GIS Cut Line= 4
     1806948.231        91180.33      1807128.87       91509.581
     1807172.429       91733.778     1807319.758       91931.072
#Sta/Elev= 30
     9.9 1841.23    29.6    1840    88.9 1821.92   108.7 1821.01   128.5 1813.03
   148.2 1811.13     168 1801.19   227.3 1788.46   237.2 1780.78     257 1779.37
   276.7 1770.85   316.3  1763.2   509.5 1753.92  523.97 1752.15   534.4 1753.86
   544.4  1754.4   564.2 1773.18   584.1 1778.13     594 1788.17   613.8 1792.91
   643.3 1814.33     663 1816.79   682.7 1838.45   702.4 1840.52     732 1861.87
   751.7 1868.27   771.4 1881.25   791.1 1885.72   810.8 1898.76   850.2 1910.58
#Mann= 3 , 0 , 0
     9.9     .08       0   509.5    .045       0   534.4     .08       0
#XS Ineff= 2 , 0
                          538.62         1771.58
Permanent Ineff=
       F       F
Bank Sta=509.5,534.4
XS Rating Curve= 0 ,0
Exp/Cntr=0.3,0.1