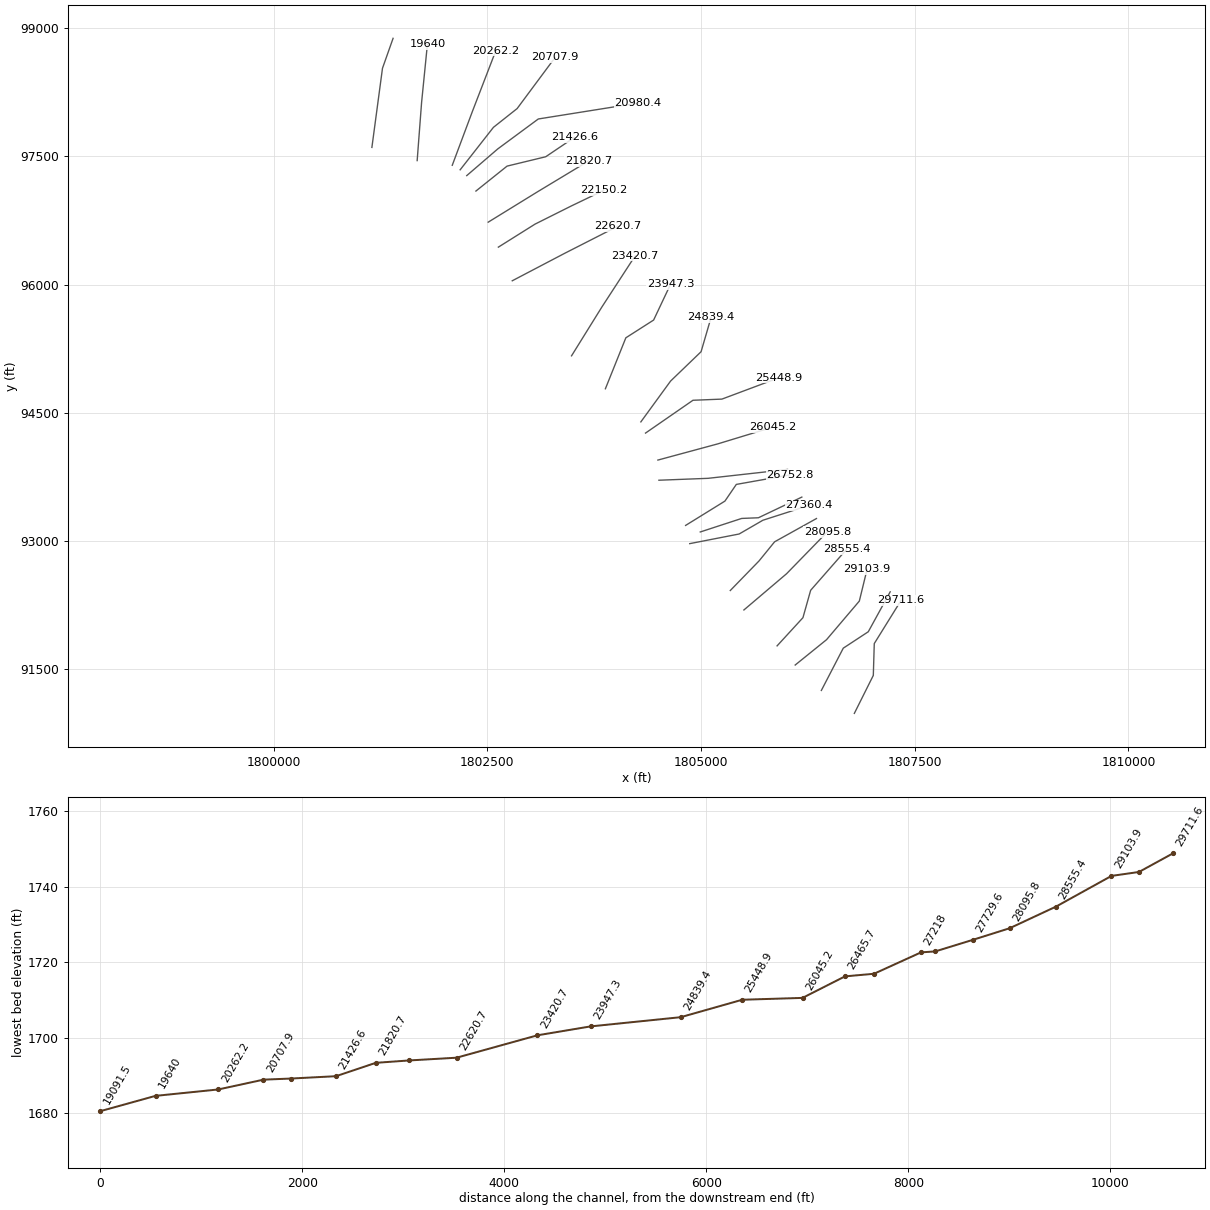
HEC-RAS study Big Creek.prj: Big Creek

--- Big Creek.g01 (geometry) --- (continued)

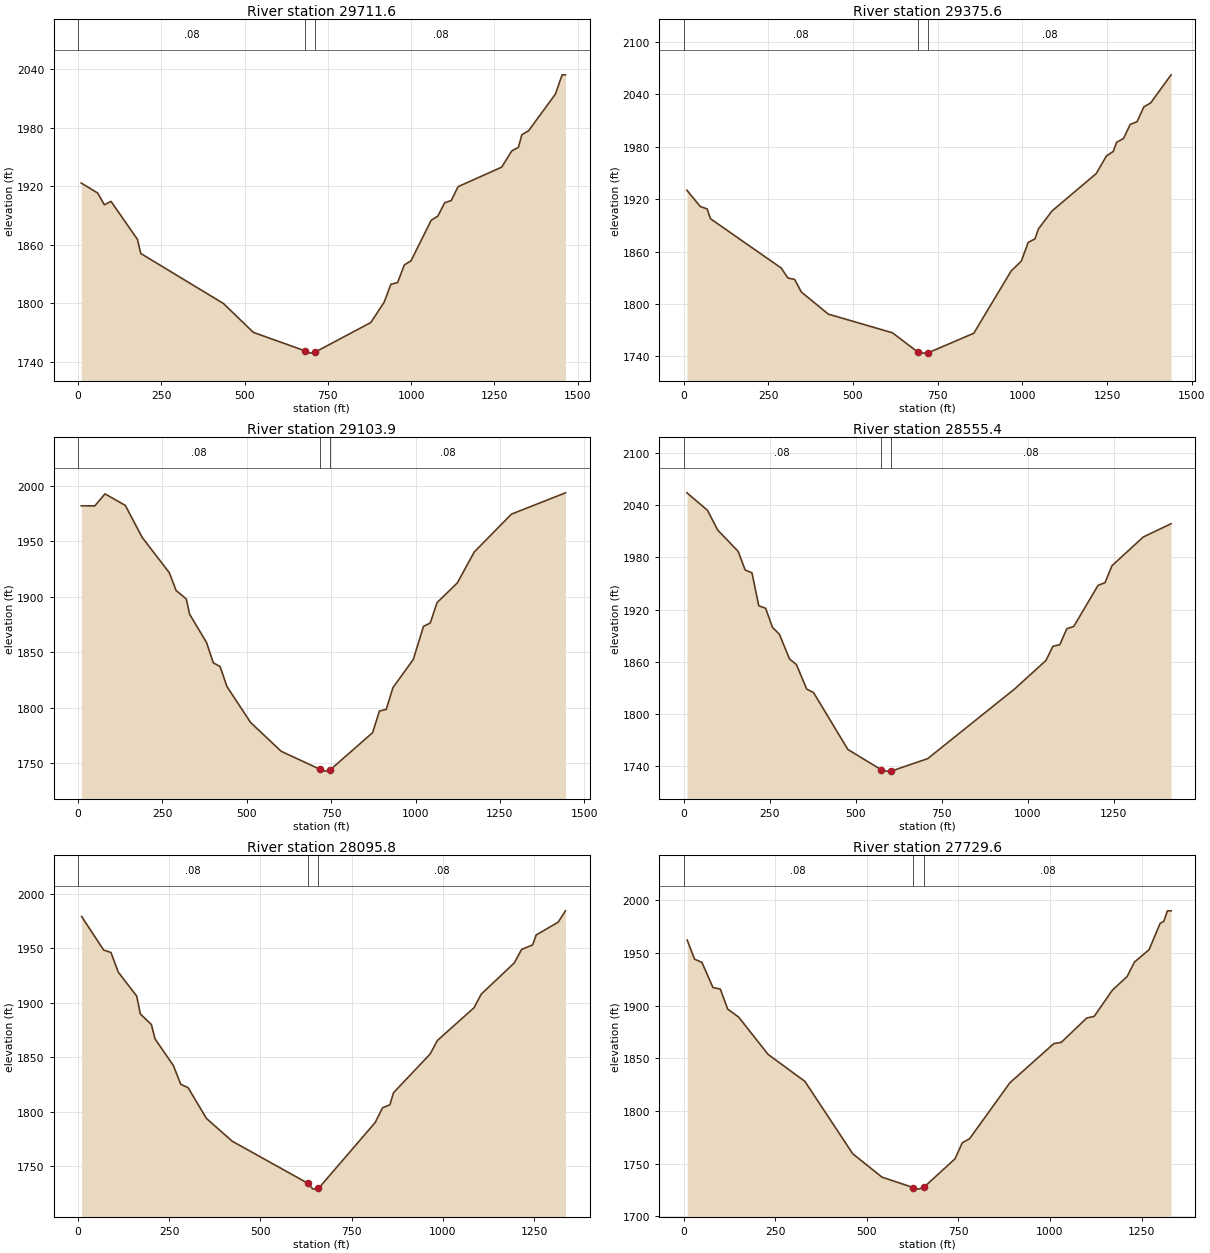
Type RM Length L Ch R = 1 ,29711.6 ,365.1,336,306.9
XS GIS Cut Line= 4
     1806793.899       90986.424      1807015.73       91430.444
     1807027.014       91802.819     1807340.672       92307.848
#Sta/Elev= 30
     9.9 1923.41    59.6  1913.1    79.4 1901.07    99.3  1904.6   178.7 1865.56
   188.6 1851.09   436.8 1799.73   526.6 1770.08   682.7 1750.96   697.7 1748.77
   712.7 1749.94     879 1780.15   919.3 1801.13   939.4 1819.49   959.6 1821.24
   979.7 1839.33   999.9 1843.61  1060.3 1885.16  1080.5 1889.51  1100.7 1903.12
  1120.8 1905.48    1141 1919.68  1271.9 1939.71  1302.2 1956.38  1322.3 1960.08
  1332.4 1973.04  1352.6 1977.04  1433.2 2014.72  1453.3  2034.5  1463.4  2034.5
#Mann= 3 , 0 , 0
       0     .08       0   682.7    .045       0   712.7     .08       0
Bank Sta=682.7,712.7
XS Rating Curve= 0 ,0
Exp/Cntr=0.3,0.1

Type RM Length L Ch R = 1 ,29375.6 ,263.3,271.8,280.3
XS GIS Cut Line= 4
     1806408.005       91254.652     1806664.231       91748.803
     1806957.062       91940.972     1807213.288       92407.671
#Sta/Elev= 30
     9.9 1930.34    49.7  1911.6    69.6    1909    79.5 1897.75   288.3 1841.28
   308.1 1829.88     328 1828.23   347.9 1813.79   427.4  1788.5   616.7 1767.14
   691.7 1745.06   706.7 1743.85   721.7 1744.17   856.8  1766.6   967.2 1837.95
   997.3 1849.25  1017.4  1870.6  1037.5 1874.69  1047.5    1886  1087.7 1906.56
  1218.3 1949.45  1248.4 1969.57  1268.5 1974.75  1278.6 1985.34  1298.7 1989.54
  1318.7 2005.72  1338.8 2008.84  1358.9 2025.76    1379 2030.31  1439.3 2062.47
#Mann= 3 , 0 , 0
       0     .08       0   691.7    .045       0   721.7     .08       0
Bank Sta=691.7,721.7
XS Rating Curve= 0 ,0
Exp/Cntr=0.3,0.1

Type RM Length L Ch R = 1 ,29103.9 ,535.4,548.5,558.4
XS GIS Cut Line= 4
     1806101.829       91551.743     1806468.452       91847.955
     1806852.111       92299.318     1806942.329       92668.874
#Sta/Elev= 30
      10 1981.89    50.1 1981.87    80.2 1992.67   140.4 1982.28   190.5 1953.38
   270.8 1921.62   290.8 1905.62   320.9 1897.95   330.9  1884.2   381.1 1858.62
   401.1 1840.38   421.2 1837.06   441.2 1819.16   511.5 1786.64   601.9 1760.71
   717.4 1744.42   732.4 1742.81   747.4 1744.01     873 1777.53     893 1796.95
   913.1 1798.43   933.2 1818.09   993.4 1843.52  1023.6 1873.28  1043.6 1876.32
  1063.7 1894.65  1123.8 1912.43  1173.8 1940.25    1284 1974.38  1444.1  1993.6
#Mann= 3 , 0 , 0
       0     .08       0   717.4    .045       0   747.4     .08       0
Bank Sta=717.4,747.4
XS Rating Curve= 0 ,0
Exp/Cntr=0.3,0.1

Type RM Length L Ch R = 1 ,28555.4 ,477.2,459.6,444.5
XS GIS Cut Line= 4
     1805890.144       91775.737     1806192.557       92105.232
     1806282.829       92425.699     1806702.597       92904.144
#Sta/Elev= 30
     9.9 2053.88    69.6 2033.81    99.4 2011.15     159 1986.59   178.9 1965.46
   198.8 1962.16   218.6 1924.35   238.5 1921.49   258.4 1899.56   278.3 1891.81
   308.1  1863.3     328 1856.95   357.8 1828.82   377.7 1824.82   477.5 1759.54
   573.5  1736.5   588.5 1734.69   603.5  1734.7   709.6 1749.06     962 1828.91
    1053 1861.58  1073.2 1877.82  1093.4  1879.7  1113.6 1897.99  1133.8  1900.6
  1204.5 1947.76  1224.7 1950.83  1244.9 1970.29  1335.8 2003.22  1416.7 2018.43
#Mann= 3 , 0 , 0
       0     .08       0   573.5    .045       0   603.5     .08       0
Bank Sta=573.5,603.5
XS Rating Curve= 0 ,0
Exp/Cntr=0.3,0.1

Type RM Length L Ch R = 1 ,28095.8 ,360.5,366.2,368.5
XS GIS Cut Line= 3
     1805501.972       92195.504     1806000.849       92619.024
     1806476.915       93107.257
#Sta/Elev= 30
    10.1 1979.12    70.5 1948.31    90.6 1946.05   110.7 1927.96   161.1  1906.1
   171.2 1889.64   201.4 1879.95   211.4 1866.82   261.8 1842.24   281.9  1825.1
     302 1822.02   352.4 1793.77   422.8 1772.95   629.3 1734.48   644.3 1728.95
   659.3 1729.56   814.9 1790.12   834.9 1803.56     855 1806.37     865 1817.38
   965.3  1852.9   985.3 1865.35  1085.6 1895.35  1105.7 1907.96  1195.9 1936.41
    1216 1948.86  1246.1 1952.96  1256.1 1962.15  1316.3 1973.85  1336.3 1984.28
#Mann= 3 , 0 , 0
       0     .08       0   629.3    .045       0   659.3     .08       0
Bank Sta=629.3,659.3
XS Rating Curve= 0 ,0
Exp/Cntr=0.3,0.1

Type RM Length L Ch R = 1 ,27729.6 ,380.9,369.2,357.5
XS GIS Cut Line= 4
     1805342.743       92423.005     1805678.685       92768.545
     1805861.053       92992.506     1806350.568       93264.459
#Sta/Elev= 30
      10 1962.07    30.1    1944    50.2 1940.92    80.3 1917.12   100.4  1915.6
   120.5 1896.64   150.6 1888.97   230.9 1853.62   331.3 1828.04   461.8 1759.41
   541.7 1737.21   626.3  1727.4   641.3 1725.86   656.3 1727.71   740.9  1754.6
   760.8 1769.82   780.7 1773.68   890.7 1826.74  1010.7  1863.9  1030.7 1865.03
  1100.7 1888.21  1120.7 1889.71  1170.7 1914.71  1210.7 1927.51  1230.7 1941.22
  1270.7 1953.01  1300.7 1977.96  1310.7 1979.79  1320.7 1989.83  1330.7 1989.83
#Mann= 3 , 0 , 0
       0     .08       0   626.3    .045       0   656.3     .08       0
Bank Sta=626.3,656.3
XS Rating Curve= 0 ,0
Exp/Cntr=0.3,0.1

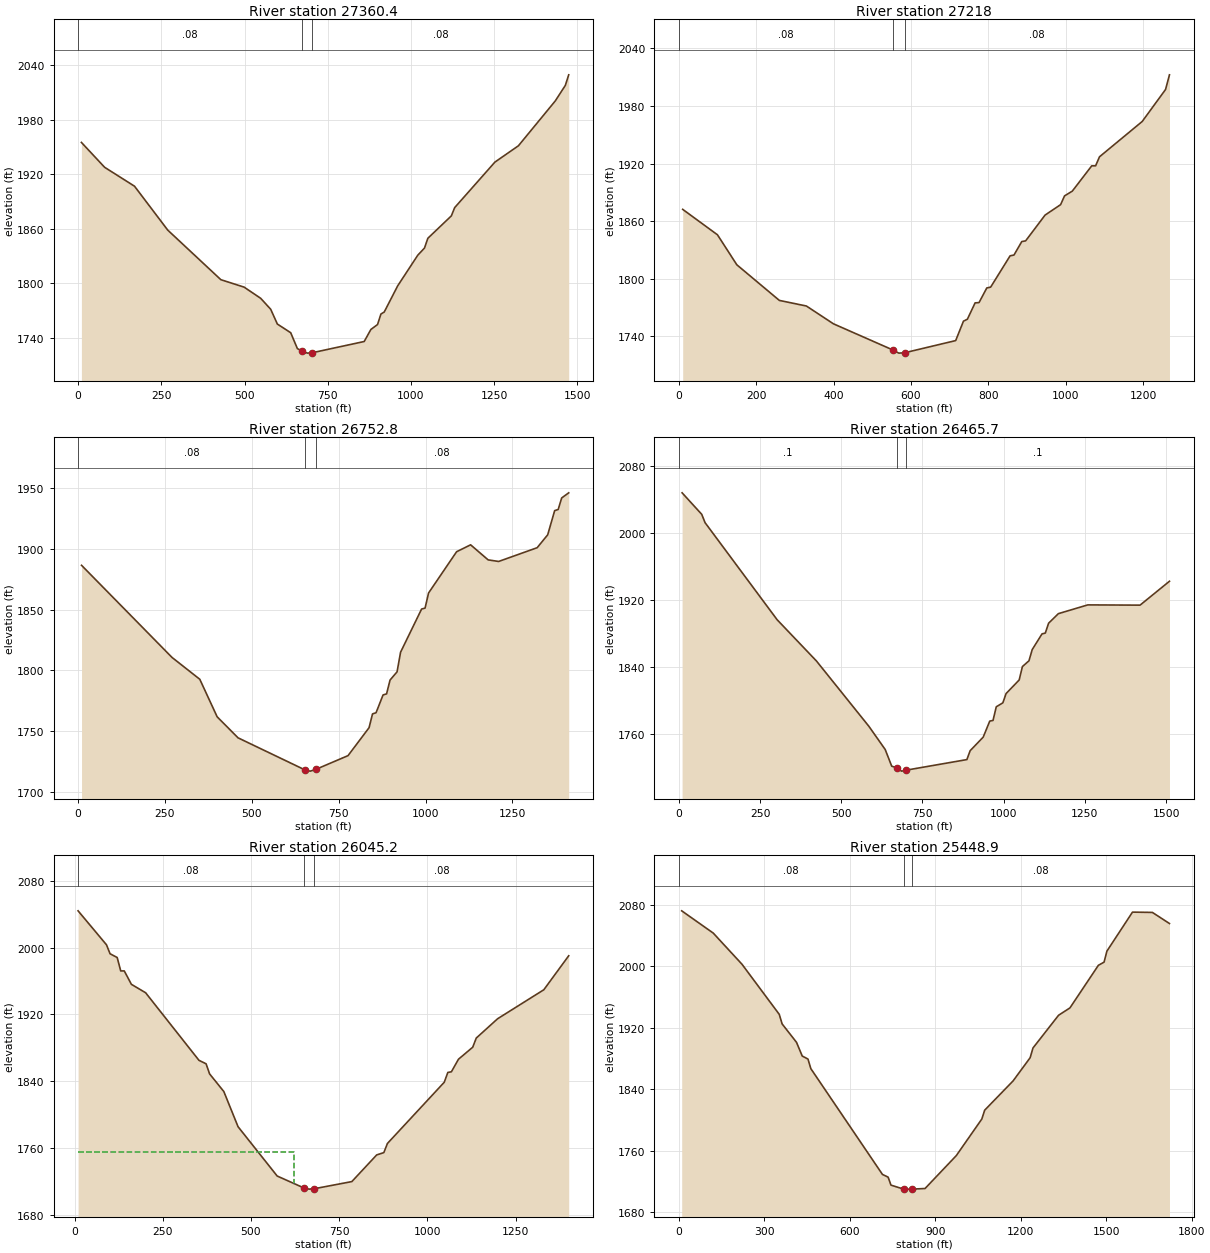
Type RM Length L Ch R = 1 ,27360.4 ,157.2,142.4,130
XS GIS Cut Line= 4
     1804868.337       92971.049     1805446.101       93083.759
     1805724.024       93244.615     1806261.296       93416.987
#Sta/Elev= 30
      10 1954.78    79.8 1927.38   169.6 1906.56   269.4 1858.25     429 1803.66
   498.9 1795.46   548.7 1783.14   578.7 1771.11   598.7 1754.84   638.8 1745.29
   658.9 1727.77     674 1725.04     689 1722.82     704 1723.29   859.6 1735.61
   879.7 1748.88   899.7 1754.29   909.8 1765.83   919.8 1768.08   960.2 1796.87
  1020.6 1830.64  1040.8 1838.51  1050.8 1849.24  1121.4  1873.9  1131.4 1882.99
  1252.3 1933.11  1322.9 1951.07  1433.7 2000.47  1463.9 2017.58    1474 2029.18
#Mann= 3 , 0 , 0
       0     .08       0     674    .045       0     704     .08       0
Bank Sta=674,704
XS Rating Curve= 0 ,0
Exp/Cntr=0.3,0.1

Type RM Length L Ch R = 1 ,27218   ,435.8,465.2,492.2
XS GIS Cut Line= 4
     1804991.348       93107.485     1805475.759        93265.66
       1805671.5       93273.569      1806179.39        93515.28
#Sta/Elev= 30
      10 1872.36    99.9 1845.84   149.9  1814.6   259.8 1777.48   329.7 1771.64
   399.7 1753.07   553.4  1725.8   568.4 1722.55   583.4 1722.92   715.5 1735.61
   735.6 1755.85   745.7 1757.87   765.7 1774.92   775.8 1775.19   795.9 1790.47
   805.9 1791.33   856.1 1823.92   866.2 1824.77   886.3 1838.79   896.3 1839.54
   946.5 1866.38   986.7 1877.28   996.8 1886.38  1016.9 1891.35  1067.1  1917.7
  1077.1 1917.71  1087.2 1927.13  1197.6 1963.94  1257.9 1997.28    1268 2012.54
#Mann= 3 , 0 , 0
       0     .08       0   553.4    .045       0   583.4     .08       0
Bank Sta=553.4,583.4
XS Rating Curve= 0 ,0
Exp/Cntr=0.3,0.1

Type RM Length L Ch R = 1 ,26752.8 ,314.1,287.1,260.2
XS GIS Cut Line= 4
     1804820.074       93184.101      1805279.77       93468.322
      1805413.23       93663.569     1806038.515       93774.786
#Sta/Elev= 30
      10 1886.55   270.2 1810.66   350.3 1792.62   400.3 1761.67   460.4 1744.34
   653.6 1717.82   668.6 1716.89   683.6 1718.25     777 1729.66   837.5 1752.69
   847.5 1764.08   857.6 1765.01   877.8 1779.71   887.9 1780.56   897.9 1791.96
   918.1 1798.74   928.2 1814.92   988.7  1850.5   998.7 1851.28  1008.8 1863.74
  1089.5 1897.76  1129.8 1903.44  1180.2 1891.03  1210.4 1889.72  1321.3 1901.06
  1351.6 1911.68  1371.7 1931.65  1381.8 1932.56  1391.9 1942.08  1412.1  1946.3
#Mann= 3 , 0 , 0
       0     .08       0   653.6    .045       0   683.6     .08       0
Bank Sta=653.6,683.6
XS Rating Curve= 0 ,0
Exp/Cntr=0.3,0.1

Type RM Length L Ch R = 1 ,26465.7 ,415.2,420.5,425.6
XS GIS Cut Line= 3
     1804507.694       93712.467     1805082.204       93734.652
     1806012.012       93838.465
#Sta/Elev= 30
    10.1 2048.26    70.6 2022.57    80.7  2012.7   302.6 1896.86   423.6 1847.65
     585 1769.73   635.3 1742.05   655.4  1722.1   670.6 1720.16   685.6  1716.2
   700.6 1717.39   886.8 1729.97   896.9 1740.59   937.1 1756.78   957.2 1775.87
   967.3 1776.69   977.3 1792.98   997.5 1797.67  1007.5 1808.74  1047.8 1824.96
  1057.8 1840.97  1077.9 1847.82    1088 1861.26  1118.2 1879.98  1128.2 1880.88
  1138.3 1892.64  1168.5 1904.09    1259 1914.54    1420 1914.25  1510.5 1942.76
#Mann= 3 , 0 , 0
       0      .1       0   670.6    .045       0   700.6      .1       0
Bank Sta=670.6,700.6
XS Rating Curve= 0 ,0
Exp/Cntr=0.3,0.1

Type RM Length L Ch R = 1 ,26045.2 ,599.5,596.3,591.4
XS GIS Cut Line= 3
     1804495.791       93948.119     1805196.046       94137.369
     1805841.735       94333.886
#Sta/Elev= 30
    10.1 2044.23    90.7 2003.45   100.7 1992.78   120.9 1988.25     131 1972.17
     141 1972.17   161.2  1956.1   201.5 1945.99   352.6 1864.98   372.8  1860.8
   382.8 1848.66   423.1 1827.54   463.4 1785.35   574.3  1726.2   649.9 1711.95
   664.9  1710.5   679.9 1711.02   785.8 1719.54   856.3 1751.54   876.5  1754.3
   886.6 1765.23  1047.7 1838.68  1057.8 1850.41  1067.9  1851.2    1088  1866.3
  1128.3 1880.66  1138.4 1891.67  1198.8  1914.8  1329.8 1949.58  1400.3 1990.33
#Mann= 3 , 0 , 0
    10.1     .08       0   649.9    .045       0   679.9     .08       0
#XS Ineff= 2 , 0
           622.9 1755.55
Permanent Ineff=
       F       F
Bank Sta=649.9,679.9
XS Rating Curve= 0 ,0
Exp/Cntr=0.3,0.1

Type RM Length L Ch R = 1 ,25448.9 ,564.6,609.6,603.8
XS GIS Cut Line= 4
     1804350.997       94263.727     1804906.173       94647.385
     1805244.695       94660.926     1805908.198       94909.176
#Sta/Elev= 30
    10.1 2071.88   120.9 2042.91   221.6 2002.47   352.5 1937.26   362.6 1924.81
     413 1900.93   433.1 1883.08   453.3 1879.14   463.3  1866.7   714.7 1729.13
   734.6 1725.61   744.6  1715.2   789.4 1710.02   794.4 1710.01   819.4 1710.05
   864.2  1710.8   973.8 1753.54  1063.5 1801.18  1073.5 1812.64  1173.3 1850.74
  1233.1  1880.9  1243.1 1893.55  1332.9  1936.1  1372.8 1945.66  1472.6 2001.04
  1492.6 2005.18  1502.5 2019.45  1592.3 2070.19  1662.2  2069.8  1722.1 2055.39
#Mann= 3 , 0 , 0
       0     .08       0   789.4    .045       0   819.4     .08       0
Bank Sta=789.4,819.4
XS Rating Curve= 0 ,0
Exp/Cntr=0.3,0.1

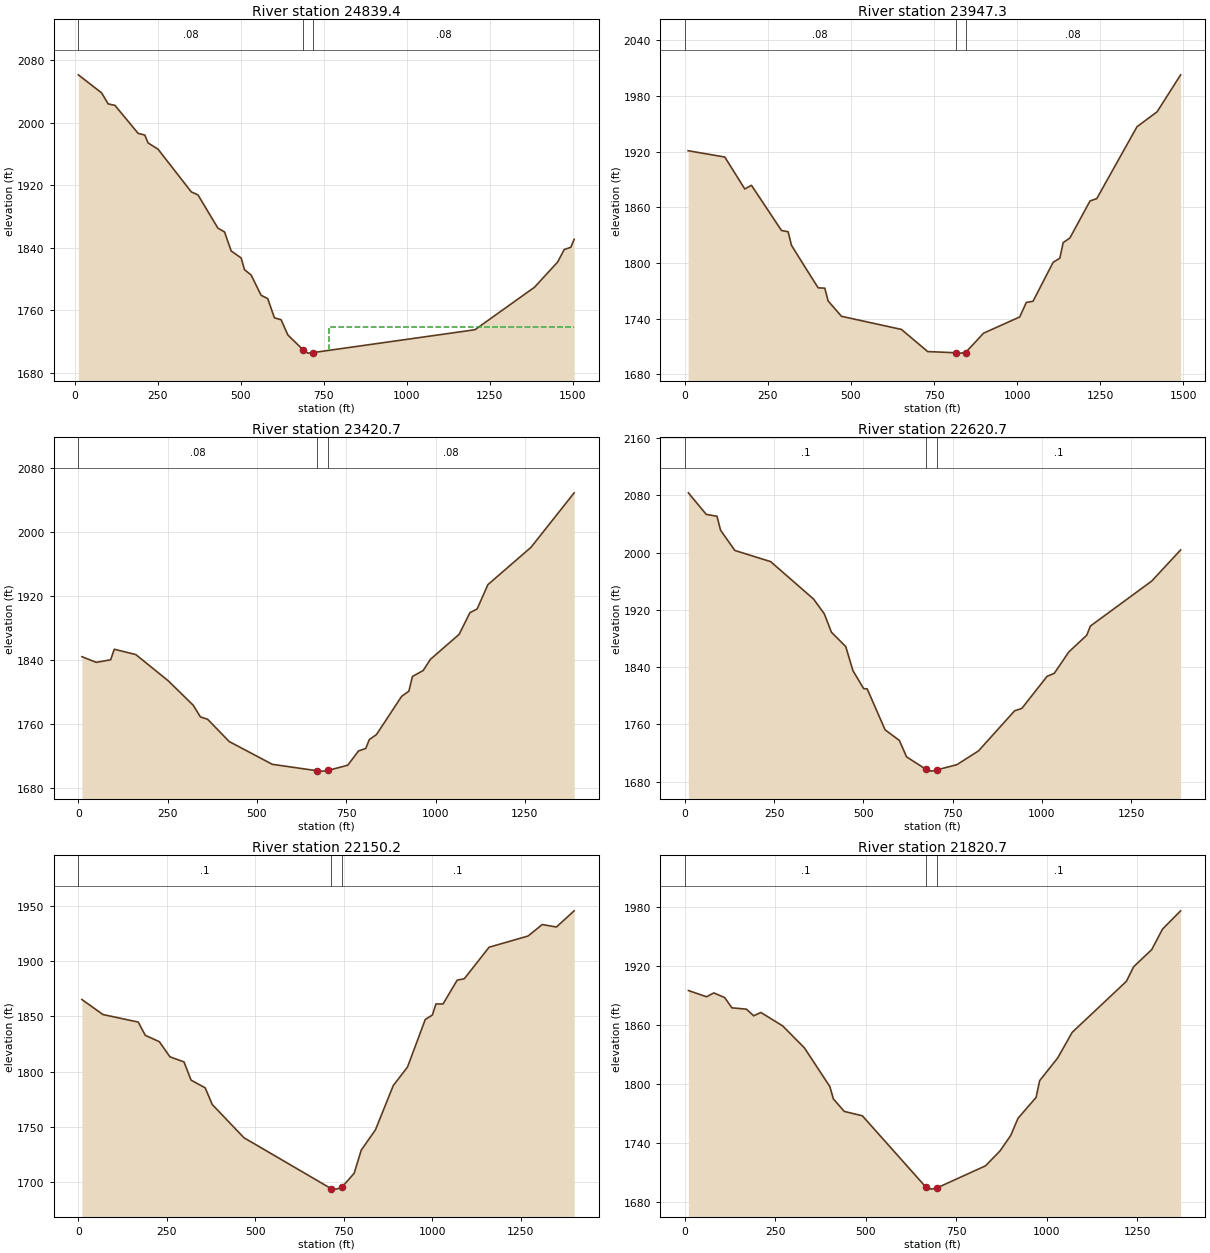
Type RM Length L Ch R = 1 ,24839.4 ,899.8,892.1,878.6
XS GIS Cut Line= 4
     1804296.451       94394.607     1804644.382       94872.086
     1805000.959       95215.122     1805118.313       95616.834
#Sta/Elev= 30
      10 2061.01    80.1 2037.97   100.1 2023.84   120.2 2022.04   190.3 1986.19
   210.3 1984.05   220.3 1973.95   250.3 1965.96   350.5 1911.37   370.5 1907.61
   430.6 1865.16   450.6 1860.22   470.6 1835.96   500.7 1826.97   510.7 1812.09
   530.7  1805.2   560.8 1779.29   580.8 1775.03   600.9 1750.49   621.1 1748.04
   641.3 1728.64   686.9 1709.79   701.9 1705.39   716.9 1706.06  1205.2 1735.28
  1384.5 1789.55  1454.3 1821.76  1474.2 1837.78  1494.1 1840.66  1504.1 1850.92
#Mann= 3 , 0 , 0
      10     .08       0   686.9    .045       0   716.9     .08       0
#XS Ineff= 2 , 0
                          764.26         1738.74
Permanent Ineff=
       F       F
Bank Sta=686.9,716.9
XS Rating Curve= 0 ,0
Exp/Cntr=0.3,0.1

Type RM Length L Ch R = 1 ,23947.3 ,513.3,526.6,539.2
XS GIS Cut Line= 4
     1803881.579       94781.813     1804120.802       95377.612
     1804445.783       95585.239     1804644.382       96005.006
#Sta/Elev= 30
      10 1920.92   120.4 1914.14   180.6 1879.72   200.6 1883.69   290.9 1835.06
     311 1833.67     321 1819.09   361.1 1796.05   401.3 1773.29   421.3 1772.91
   431.4 1759.14   471.5 1742.62   651.9 1728.48     731 1704.64   814.9 1703.34
   829.9 1702.95   844.9 1703.57   899.1 1724.44  1007.9 1741.93  1027.7 1757.55
  1047.9  1758.8  1108.4 1800.73  1128.6 1805.19  1138.7 1821.93  1158.9 1826.99
  1219.5 1866.86  1239.7 1869.34  1360.8 1946.75  1421.4  1962.9  1492.1 2002.67
#Mann= 3 , 0 , 0
       0     .08       0   814.9    .045       0   844.9     .08       0
Bank Sta=814.9,844.9
XS Rating Curve= 0 ,0
Exp/Cntr=0.3,0.1

Type RM Length L Ch R = 1 ,23420.7 ,815.9,800,784.4
XS GIS Cut Line= 3
     1803485.581       95166.923     1803841.311       95739.126
     1804230.821       96337.886
#Sta/Elev= 30
    10.1 1843.68    50.3 1836.62    90.5 1839.82   100.6 1853.03   160.9 1846.37
   251.4 1813.69   321.8 1782.92   341.9 1768.35     362 1765.43   422.4 1737.59
     543 1709.11   668.8 1701.04   683.8 1700.59   698.8 1701.43   754.3    1708
   784.4 1725.83   804.6 1728.93   814.6 1740.04   834.7 1746.34   905.2 1794.17
   925.3 1800.51   935.3 1818.92   965.5 1826.45   985.6 1840.33  1066.1 1871.69
  1096.3 1898.76  1116.4 1903.35  1146.6  1933.8  1267.3 1980.49  1388.1 2048.63
#Mann= 3 , 0 , 0
       0     .08       0   668.8    .045       0   698.8     .08       0
Bank Sta=668.8,698.8
XS Rating Curve= 0 ,0
Exp/Cntr=0.3,0.1

Type RM Length L Ch R = 1 ,22620.7 ,471.1,470.5,470.3
XS GIS Cut Line= 3
     1802792.102       96044.501     1803404.633       96365.212
     1804026.202        96681.78
#Sta/Elev= 30
      10 2083.54    60.1 2053.43    90.2  2050.8   100.2 2031.32   140.3    2003
   240.5 1987.41   360.7 1935.13   390.8  1914.5   410.8 1888.73   450.9 1868.71
     471 1835.13     501 1809.95     511 1809.55   561.1 1752.39   601.2  1737.5
   621.3  1714.6   676.4 1696.97   691.4 1694.66   706.4 1696.42   762.2 1703.68
   822.8 1722.94   923.9 1778.94   944.1 1782.29  1014.9 1827.15  1035.1 1831.34
  1075.6 1861.09  1126.1 1884.61  1136.2 1897.38  1308.1 1960.27    1389 2003.74
#Mann= 3 , 0 , 0
       0      .1       0   676.4    .045       0   706.4      .1       0
Bank Sta=676.4,706.4
XS Rating Curve= 0 ,0
Exp/Cntr=0.3,0.1

Type RM Length L Ch R = 1 ,22150.2 ,326.8,329.5,331.9
XS GIS Cut Line= 4
     1802629.485        96437.79     1803059.455       96707.433
     1803482.138       96918.774     1803861.094       97100.964
#Sta/Elev= 30
      10 1865.34    69.7 1851.73   169.2 1844.93   189.1 1832.97   228.9 1827.17
   258.7 1813.54   298.5 1808.93   318.4 1792.46   358.3 1785.51   378.2 1770.46
   467.7 1740.42   713.7 1694.45   728.7 1693.93   743.7 1695.41     779 1708.17
   799.1 1729.13   839.3 1747.53   889.6 1787.53   929.8 1804.26   980.1 1847.32
  1000.1 1851.29  1010.1 1861.27  1030.2  1861.3  1070.2 1882.82  1090.2 1884.06
  1160.3 1912.58  1270.4 1922.72  1310.5 1933.08  1350.5 1930.86  1400.6 1945.48
#Mann= 3 , 0 , 0
       0      .1       0   713.7    .045       0   743.7      .1       0
Bank Sta=713.7,743.7
XS Rating Curve= 0 ,0
Exp/Cntr=0.3,0.1

Type RM Length L Ch R = 1 ,21820.7 ,403.4,394.1,385.2
XS GIS Cut Line= 3
     1802510.667       96729.709     1803090.847       97086.856
     1803681.069       97442.696
#Sta/Elev= 30
      10 1895.09    60.1 1888.76    80.2 1892.67   110.2 1887.95   130.2 1877.51
   170.3 1876.15   190.4  1869.4   210.4 1872.77   270.5 1859.15   330.6 1836.85
   400.8 1797.63   410.8 1784.91   440.8 1772.28   490.9 1767.78   666.3  1695.4
   681.3  1693.3   696.3 1694.41   831.1 1716.96   871.1 1732.02     901  1747.9
     921 1765.27     971  1786.5   980.9 1803.51  1030.9 1826.68  1070.8 1852.61
  1220.7 1904.47  1240.6 1919.22  1290.6 1936.65  1320.5 1957.53  1370.5 1976.06
#Mann= 3 , 0 , 0
       0      .1       0   666.3    .045       0   696.3      .1       0
Bank Sta=666.3,696.3
XS Rating Curve= 0 ,0
Exp/Cntr=0.3,0.1

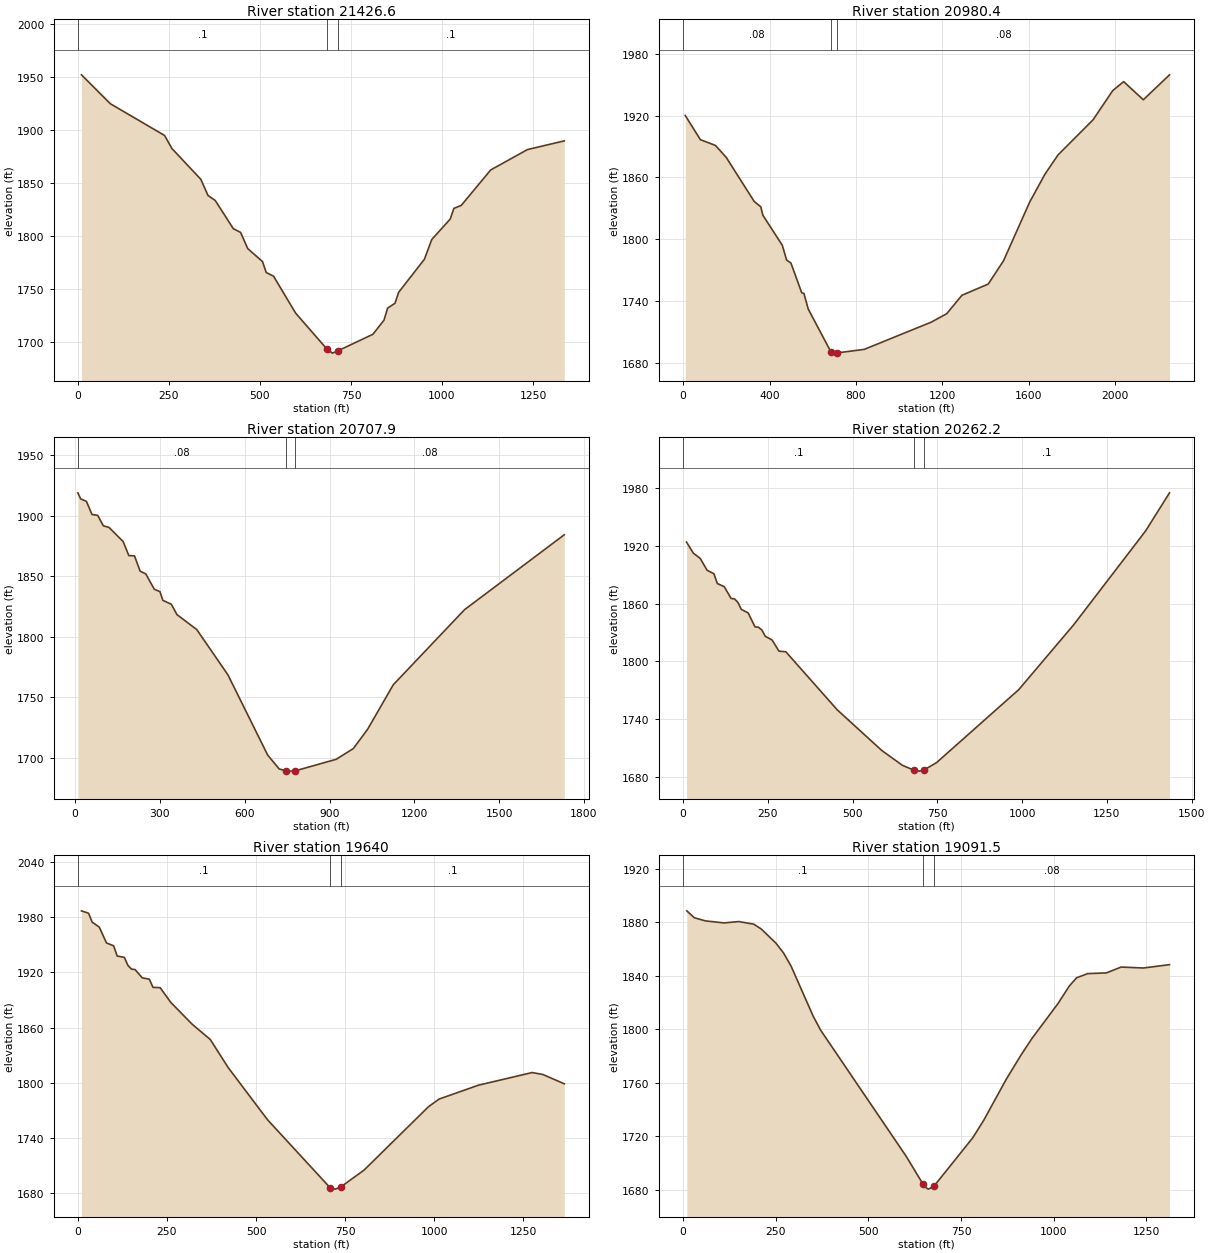
Type RM Length L Ch R = 1 ,21426.6 ,425.2,446.2,380.1
XS GIS Cut Line= 4
     1802367.131       97093.677     1802731.512       97385.182
     1803183.345       97494.496     1803518.576       97720.413
#Sta/Elev= 30
     9.9 1952.24    89.4 1924.93   238.3 1895.01   258.1  1882.8   337.6 1853.74
   357.4 1838.45   377.3  1833.7   426.9 1807.14   446.8 1803.65   466.6 1788.32
   507.1 1776.12   517.2 1765.84   537.4 1762.34     598 1727.49   684.1 1693.55
   699.1 1689.76   714.1 1691.91   810.2 1707.52   840.6 1720.78   850.7 1732.27
   870.9 1736.77     881 1747.16   951.7 1778.31   971.9 1796.94  1022.5 1816.17
  1032.6 1826.27  1052.8 1829.06  1133.6 1862.49  1234.7 1881.74  1335.8 1889.95
#Mann= 3 , 0 , 0
       0      .1       0   684.1    .045       0   714.1      .1       0
Bank Sta=684.1,714.1
XS Rating Curve= 0 ,0
Exp/Cntr=0.3,0.1

Type RM Length L Ch R = 1 ,20980.4 ,265.5,272.5,358.6
XS GIS Cut Line= 4
      1802259.71       97274.122      1802622.89       97586.477
     1803096.821       97936.283     1804264.722        98122.47
#Sta/Elev= 30
      10 1920.26    79.8 1896.73   149.7 1891.09   199.6 1879.46   329.3 1836.52
   359.3 1831.49   369.2  1823.2   459.1    1794     479 1779.61     499 1776.72
   548.9 1747.79   558.9 1747.26   578.9 1732.09   683.7 1690.45   698.7 1689.14
   713.7 1689.39   838.4  1692.8  1148.9 1719.33  1219.7 1727.47  1290.5 1745.44
  1411.7 1756.26  1482.5 1778.89  1603.8 1836.05  1674.6 1863.23  1735.2 1881.97
  1896.9    1916  1987.9 1944.41  2038.5 1953.12  2129.4  1935.5  2250.7 1959.75
#Mann= 3 , 0 , 0
       0     .08       0   683.7    .045       0   713.7     .08       0
Bank Sta=683.7,713.7
XS Rating Curve= 0 ,0
Exp/Cntr=0.3,0.1

Type RM Length L Ch R = 1 ,20707.9 ,430.3,445.7,451.6
XS GIS Cut Line= 4
     1802182.762       97342.169     1802572.063       97838.668
     1802849.256       98058.125     1803294.243       98656.763
#Sta/Elev= 30
      10 1918.87      20 1913.84    40.1 1911.85    60.1 1900.95    80.1 1900.26
   100.1 1891.63   120.2 1890.27   170.2  1878.6   190.3 1866.98   210.3 1866.77
   230.3 1854.12   250.4 1851.81   280.4 1839.16   300.4 1837.19   310.5 1830.04
   340.5  1826.8   360.5 1818.24   430.6 1805.83   540.8 1768.41   681.4  1702.1
   721.8 1690.69   747.2  1688.9  762.13 1688.84   777.2 1688.97   923.9 1698.63
   984.5 1707.53  1034.9 1723.46  1125.6 1760.24  1377.6 1822.28  1730.4 1884.21
#Mann= 3 , 0 , 0
      10     .08       0   747.2    .045       0   777.2     .08       0
Bank Sta=747.2,777.2
XS Rating Curve= 0 ,0
Exp/Cntr=0.3,0.1

Type RM Length L Ch R = 1 ,20262.2 ,613.4,622.2,631.1
XS GIS Cut Line= 3
     1802090.171       97394.783     1802323.813       98019.213
     1802600.273       98735.751
#Sta/Elev= 30
    10.1 1923.73    30.3 1912.25    50.5  1906.8    70.7  1894.6    90.9 1890.91
     101 1880.73   121.2 1877.58   141.4 1865.39   151.5 1864.84   161.6 1861.24
   171.7    1854   191.9 1850.28   212.1 1835.83   222.2 1835.49   232.3  1832.6
   242.4 1826.08   262.6 1822.18   282.8 1810.66     303 1810.02   454.6 1749.84
   585.9  1707.7   646.5 1692.36     682 1687.01     697 1686.25     712 1687.76
   747.6 1695.08   990.1 1770.78  1151.8  1837.9    1364 1935.24  1434.7 1974.83
#Mann= 3 , 0 , 0
       0      .1       0     682    .045       0     712      .1       0
Bank Sta=682,712
XS Rating Curve= 0 ,0
Exp/Cntr=0.3,0.1

Type RM Length L Ch R = 1 ,19640   ,553.4,548.5,543.7
XS GIS Cut Line= 3
     1801679.649       97449.454     1801731.527       98130.211
     1801799.434       98809.284
#Sta/Elev= 30
      10 1986.71    30.1 1984.09    40.2 1974.41    60.2 1969.02    80.3 1951.85
   100.4 1948.73   110.4 1937.63   130.5 1936.18   140.6 1927.36   150.6 1923.41
   160.6 1922.96   180.7 1913.98   200.8 1912.43   210.8 1903.61   230.9  1903.3
     261 1887.21   321.3 1863.41   371.5 1847.09   421.7 1816.64   532.1 1759.97
   707.9  1686.1   722.9 1684.55   737.9  1686.9   803.2  1705.2   983.8 1773.93
  1013.9 1782.35  1124.3 1797.39  1274.9 1811.11    1305 1809.01  1365.2 1798.91
#Mann= 3 , 0 , 0
       0      .1       0   707.9    .045       0   737.9      .1       0
Bank Sta=707.9,737.9
XS Rating Curve= 0 ,0
Exp/Cntr=0.3,0.1

Type RM Length L Ch R = 1 ,19091.5 ,404.6,404.6,404.7
XS GIS Cut Line= 3
     1801150.097       97603.811     1801273.987       98529.339
     1801397.877       98879.145
#Sta/Elev= 30
      10  1888.5    30.1 1883.37    60.2 1880.97   110.4 1879.47   150.6 1880.48
   190.8 1878.51   210.9 1874.91     251 1864.23   271.1 1856.98   291.2 1847.27
   351.4 1809.52   371.5 1799.15   601.7 1705.14   646.7 1684.55   651.7 1682.18
   661.7 1680.48   676.7 1682.57   781.6 1718.85   811.6  1732.1   871.5 1762.36
   911.5 1780.55   941.5 1793.15  1011.7  1819.2  1041.8 1832.16  1061.8 1838.45
  1091.9 1841.57  1142.1  1842.1  1182.2 1846.48  1242.4 1845.77  1312.6 1848.28
#Mann= 3 , 0 , 0
       0      .1       0   646.7    .045       0   676.7     .08       0
Bank Sta=646.7,676.7
XS Rating Curve= 0 ,0
Exp/Cntr=0.3,0.1