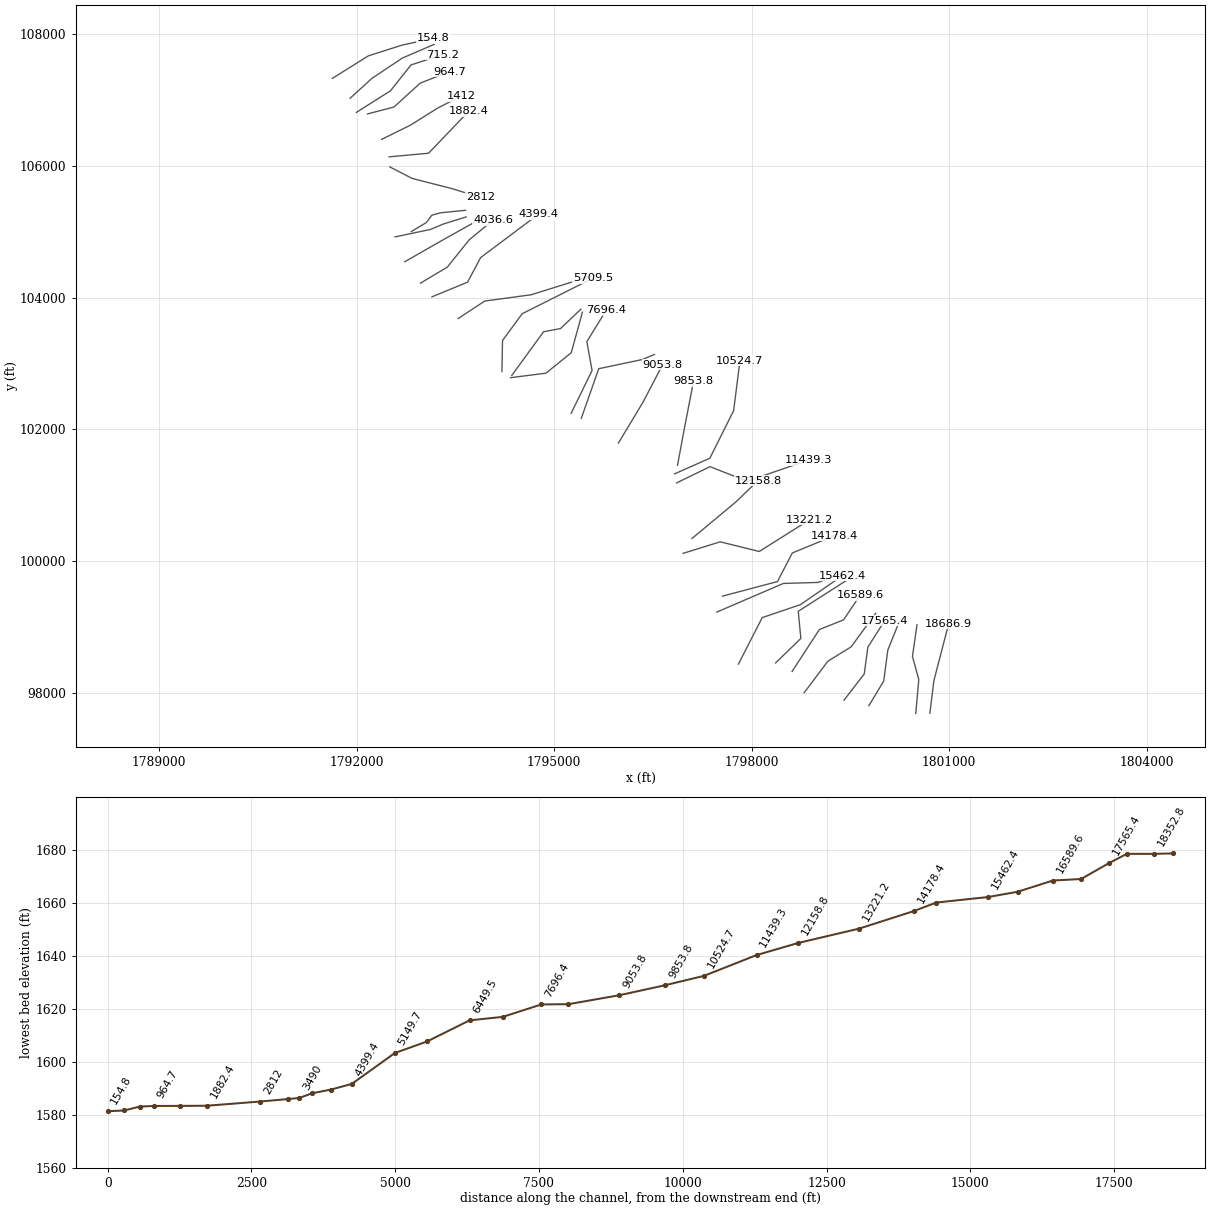
HEC-RAS study Big Creek.prj: Big Creek

--- Big Creek.g01 (geometry) --- (continued)

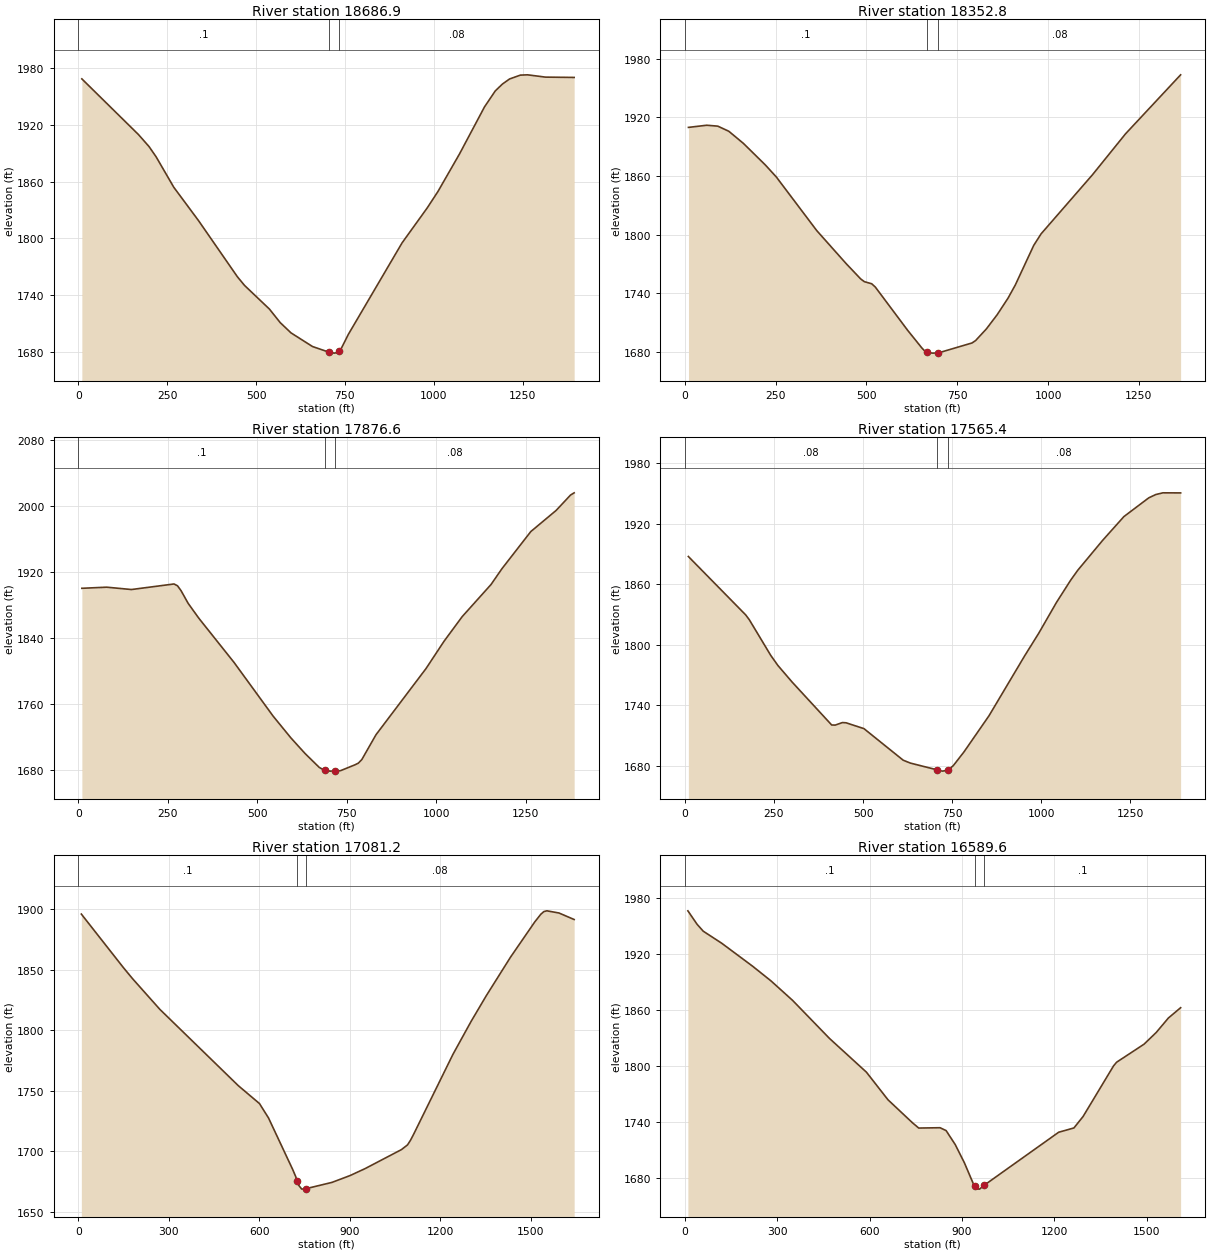
Type RM Length L Ch R = 1 ,18686.9 ,318.4,334.1,349.9
XS GIS Cut Line= 3
     1800706.168       97689.027     1800766.612       98182.832
     1800992.293       99051.705
#Sta/Elev= 30
     9.9 1968.61   169.1 1909.76     199 1897.01   218.9 1886.17   268.6 1853.99
   338.3 1818.65   447.7 1759.27   467.6  1750.2   537.8 1725.12   568.1 1710.82
   598.4 1699.99   658.9 1685.55   704.4 1679.67   719.4 1678.56   729.5  1679.1
   734.4 1681.12   739.6 1683.27   759.7 1698.33     911 1795.18   981.6 1832.05
  1011.9 1849.48  1072.4 1889.09    1143 1939.01  1173.3  1955.9  1193.5 1963.19
  1213.6 1968.53  1243.9 1972.59  1264.1 1972.89  1314.5 1970.46  1395.2 1970.13
#Mann= 3 , 0 , 0
       0      .1       0   704.4    .045       0   734.4     .08       0
Bank Sta=704.4,734.4
XS Rating Curve= 0 ,0
Exp/Cntr=0.3,0.1

Type RM Length L Ch R = 1 ,18352.8 ,488.2,476.2,464.3
XS GIS Cut Line= 4
      1800491.92       97687.765     1800537.675       98200.218
      1800441.59       98552.529     1800510.222       99032.954
#Sta/Elev= 30
    10.1 1909.86    60.5 1912.06    90.8 1911.13   121.1  1905.9   161.4 1893.43
   221.9 1871.28   252.2  1858.9   363.2 1804.07   443.9  1770.3   484.2 1754.48
   494.3 1751.67   514.5 1749.53   524.4 1746.19   613.2 1701.96   652.7 1683.66
   662.5 1679.85   667.3 1679.19   682.3  1678.4   697.3 1678.55   790.8 1688.83
   800.7 1691.32   830.3 1703.25   859.9 1717.75   889.8 1734.73     910 1748.36
   960.6 1788.86   980.8 1800.67  1122.3 1861.27  1213.3 1903.24    1365 1963.75
#Mann= 3 , 0 , 0
       0      .1       0   667.3    .045       0   697.3     .08       0
Bank Sta=667.3,697.3
XS Rating Curve= 0 ,0
Exp/Cntr=0.3,0.1

Type RM Length L Ch R = 1 ,17876.6 ,311.3,311.2,311.1
XS GIS Cut Line= 4
     1799779.294       97804.609     1800004.937        98177.19
     1800067.455       98648.676     1800244.092       99089.179
#Sta/Elev= 30
     9.9    1900    79.2 1901.35   148.5 1898.51   267.3 1905.24   277.2 1903.05
   287.1 1897.14   306.9 1881.81   336.6 1863.84   435.6 1809.91   544.6 1744.97
   594.1 1718.69   633.8  1699.7   673.4  1682.9   688.1 1679.34   703.1  1678.4
   718.1 1678.41   732.8 1678.95   772.5 1685.93   782.4 1687.99   792.3 1692.39
   831.9 1722.48   971.8 1802.74  1022.3 1835.92  1072.8 1865.63  1153.5 1904.61
  1183.8 1923.65  1264.6 1968.74  1335.3 1994.35  1375.7 2013.01  1385.8 2015.72
#Mann= 3 , 0 , 0
       0      .1       0   688.1    .045       0   718.1     .08       0
Bank Sta=688.1,718.1
XS Rating Curve= 0 ,0
Exp/Cntr=0.3,0.1

Type RM Length L Ch R = 1 ,17565.4 ,511.4,484.2,457
XS GIS Cut Line= 4
     1799402.958       97889.086     1799709.514       98287.152
      1799764.42       98694.369     1800020.646        99097.01
#Sta/Elev= 30
      10 1887.39   170.8 1829.56   180.9  1824.8   241.2 1789.39   261.3 1779.43
   301.5 1762.88     412 1720.56     422 1720.47   442.1 1722.97   452.2 1722.75
   502.4 1716.97   612.7 1685.66   632.7 1682.84   707.9 1676.15   722.9 1674.89
   737.9 1675.84     753 1680.31     783 1693.93   853.2 1729.71   953.1 1788.99
   992.9 1811.54  1042.6 1842.03  1082.4 1864.03  1102.2 1873.81  1171.8 1903.33
  1231.5 1926.89  1301.1 1945.43    1321 1948.74  1340.9 1950.43  1390.6 1950.35
#Mann= 3 , 0 , 0
       0     .08       0   707.9    .045       0   737.9     .08       0
Bank Sta=707.9,737.9
XS Rating Curve= 0 ,0
Exp/Cntr=0.3,0.1

Type RM Length L Ch R = 1 ,17081.2 ,497.6,491.6,485.5
XS GIS Cut Line= 4
     1798797.541       98002.287     1799158.632        98481.86
     1799508.438       98696.257     1799882.127       99206.718
#Sta/Elev= 30
      10 1896.03   150.1 1851.58   180.1 1842.57   270.1 1817.38   530.3 1754.31
   600.3 1739.57   630.3 1727.68   710.4 1685.12   720.4 1679.28   725.4 1675.66
   730.4 1672.05   740.4 1668.91   755.4 1669.34   840.5 1674.46   900.5  1680.1
   950.6 1685.88  1070.8 1701.54  1090.9 1705.41    1101 1709.33    1111  1714.1
  1241.6 1780.25  1301.8 1807.46    1352 1828.63  1432.3 1860.45  1512.7 1889.56
  1532.8 1895.92  1542.8 1898.07  1552.8 1898.71    1593 1896.91  1643.2 1891.55
#Mann= 3 , 0 , 0
       0      .1       0   725.4    .045       0   755.4     .08       0
Bank Sta=725.4,755.4
XS Rating Curve= 0 ,0
Exp/Cntr=0.3,0.1

Type RM Length L Ch R = 1 ,16589.6 ,572.2,613.3,654
XS GIS Cut Line= 4
      1798613.84       98325.071     1799028.865       98961.433
     1799395.597       99108.126     1799649.489       99486.142
#Sta/Elev= 30
      10 1966.52      40 1952.06      60 1944.67     120 1931.77   219.9 1907.25
   279.9 1891.45   349.9 1870.61   469.8 1829.81   589.8 1793.65   659.8 1764.06
   739.7 1739.31   759.7 1733.77   828.9 1734.12   848.6 1731.04   878.2 1716.05
   907.9 1696.58   937.5 1673.66   942.2 1671.29   947.4 1668.67   957.2 1668.33
   972.2 1672.48  1214.1 1729.28  1263.6 1733.88  1293.3 1746.12  1392.3 1800.38
  1402.2  1804.3  1491.3 1823.63  1530.9 1836.19  1570.5 1851.71  1610.1 1862.71
#Mann= 3 , 0 , 0
       0      .1       0   942.2    .045       0   972.2      .1       0
Bank Sta=942.2,972.2
XS Rating Curve= 0 ,0
Exp/Cntr=0.3,0.1

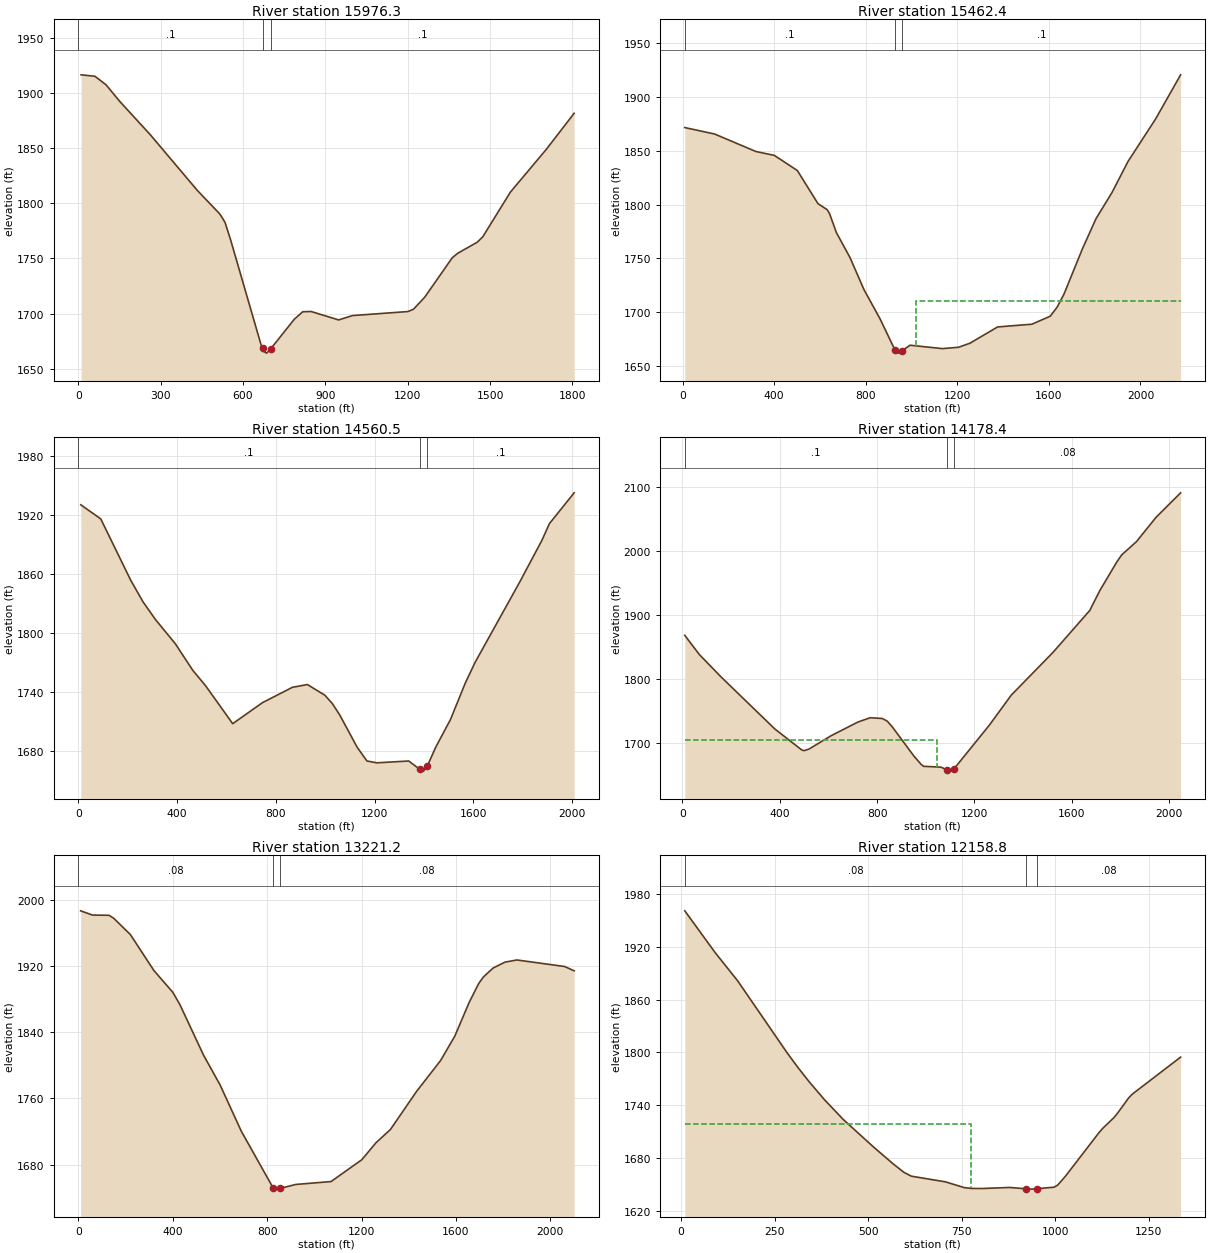
Type RM Length L Ch R = 1 ,15976.3 ,554.5,513.9,473.3
XS GIS Cut Line= 4
     1798363.105        98453.65     1798746.763       98826.024
     1798707.269       99237.893     1799429.449       99700.539
#Sta/Elev= 30
    10.1 1916.47    60.5 1915.16   100.9 1907.44   151.3 1892.26   262.3 1862.11
   433.8 1811.56   514.5 1790.51   524.6 1786.74   534.7 1782.42   554.8 1766.74
   665.8 1671.48     671 1668.41   675.9 1665.52     686 1664.08     701 1668.06
   786.9 1694.86   817.2 1701.57   847.5 1701.86   948.4 1694.18   998.9 1698.15
  1200.7 1701.78  1220.8 1703.89  1261.2 1714.61  1362.1 1750.57  1382.3 1754.69
  1452.9 1764.64  1473.1 1769.51    1574 1810.16  1705.2 1849.05  1806.1 1881.62
#Mann= 3 , 0 , 0
       0      .1       0     671    .045       0     701      .1       0
Bank Sta=671,701
XS Rating Curve= 0 ,0
Exp/Cntr=0.3,0.1

Type RM Length L Ch R = 1 ,15462.4 ,910.7,902,893.2
XS GIS Cut Line= 4
     1797798.901       98436.724     1798159.992       99141.978
     1798741.121       99339.449     1799374.145       99776.377
#Sta/Elev= 30
      10 1871.59   140.4 1865.58   320.9 1849.33   401.2 1845.74   501.5 1831.69
   591.7 1800.91   631.8 1795.32   641.9 1791.79     672 1774.08   732.1 1750.59
   792.3 1721.17   862.8 1693.88   928.2 1664.85   943.2  1662.1   958.2 1664.22
   993.6 1669.44  1134.4  1666.3  1204.8 1667.52  1255.2 1671.29  1375.9 1686.41
    1526 1688.96  1605.9 1696.39  1635.8 1704.74  1665.8  1716.8  1745.7 1758.61
  1805.7 1786.95  1875.6 1811.25  1945.5 1840.06  2065.4 1879.37  2175.3 1920.57
#Mann= 3 , 0 , 0
      10      .1       0   928.2    .045       0   958.2      .1       0
#XS Ineff= 2 , 0
                          1020.9         1710.76
Permanent Ineff=
       F       F
Bank Sta=928.2,958.2
XS Rating Curve= 0 ,0
Exp/Cntr=0.3,0.1

Type RM Length L Ch R = 1 ,14560.5 ,349.6,382.1,414.6
XS GIS Cut Line= 4
     1797471.663       99226.608     1798481.588       99661.045
     1799009.233       99676.247     1799363.372       99817.384
#Sta/Elev= 30
    10.1 1930.14    90.8 1915.88   211.8 1853.86   262.2 1831.66   312.7 1813.73
   393.4 1789.06     464 1762.13   514.4 1746.98   625.3 1708.15   746.4 1729.52
   867.4 1745.05   927.9 1747.84   998.5 1737.05  1028.8 1728.64  1059.1 1716.93
  1129.3 1684.32  1169.1 1670.32    1209 1668.44  1338.4 1670.29  1383.2 1661.87
  1398.2 1660.02  1413.2 1664.97    1448 1684.41  1507.7 1712.47  1567.5 1749.34
  1607.3  1770.4  1787.8 1851.73  1878.1 1894.22  1908.2 1911.04  2008.5  1942.3
#Mann= 3 , 0 , 0
       0      .1       0  1383.2    .045       0  1413.2      .1       0
Bank Sta=1383.2,1413.2
XS Rating Curve= 0 ,0
Exp/Cntr=0.3,0.1

Type RM Length L Ch R = 1 ,14178.4 ,997.9,957.2,949.1
XS GIS Cut Line= 4
     1797558.256       99468.832     1798391.315       99689.255
     1798616.996      100123.692     1799260.188      100388.868
#Sta/Elev= 30
      10 1868.33    70.1 1838.36   160.3 1803.12   380.8 1722.23     491 1689.74
     501 1688.76     521 1691.38   611.2 1712.05   721.4 1733.32   771.5 1740.03
   821.6 1738.84   841.7 1734.68   861.7 1726.14   951.6 1680.17   981.6 1667.11
   991.6  1664.3  1061.5 1663.09  1086.5 1659.16  1101.5 1656.84  1116.5 1660.62
  1261.4 1728.56  1351.3 1775.27  1522.7 1841.85  1673.9 1907.21  1714.3 1937.63
  1784.8  1982.7    1805  1993.8  1865.5 2014.35  1946.2 2052.35    2047 2090.43
#Mann= 3 , 0 , 0
      10      .1       0  1086.5    .045       0  1116.5     .08       0
#XS Ineff= 2 , 0
         1046.58 1705.24
Permanent Ineff=
       F       F
Bank Sta=1086.5,1116.5
XS Rating Curve= 0 ,0
Exp/Cntr=0.3,0.1

Type RM Length L Ch R = 1 ,13221.2 ,1032.2,1062.4,1101.1
XS GIS Cut Line= 4
     1796958.238       100118.05     1797522.442      100292.953
     1798114.855       100146.26      1798876.53      100625.833
#Sta/Elev= 30
      10  1987.1    60.1 1981.96   130.2 1981.67   150.2 1978.05   220.3 1958.47
   320.4 1914.77   400.5 1888.46   430.5 1873.52   530.6 1812.38   600.7 1776.34
   690.7 1720.27   825.8 1651.52   840.8 1650.19   855.8 1651.13   920.9 1655.82
  1070.9 1659.37    1201 1685.72  1261.7 1706.45  1322.4 1722.34  1433.6 1768.59
  1534.7 1805.69  1595.4 1835.43  1656.1 1876.13  1696.5 1899.04  1716.8 1907.11
  1757.2 1917.75  1807.8 1924.97  1858.4 1927.61  2060.6  1919.7  2101.1  1914.5
#Mann= 3 , 0 , 0
       0     .08       0   825.8    .045       0   855.8     .08       0
Bank Sta=825.8,855.8
XS Rating Curve= 0 ,0
Exp/Cntr=0.3,0.1

Type RM Length L Ch R = 1 ,12158.8 ,757.9,719.5,687.2
XS GIS Cut Line= 3
     1797093.647      100343.731     1797760.413      100898.972
     1798096.406      101223.498
#Sta/Elev= 30
    10.1 1960.72    90.8 1913.51   151.3 1881.29   282.5  1800.1   312.8 1782.65
     343 1766.32   383.4 1746.25   433.8  1723.7   514.6  1692.5     565 1674.08
   595.3 1663.89   615.4 1659.45   706.3 1653.06   756.7 1646.48   776.9 1645.53
   807.1 1645.49   877.6 1646.66   922.3 1645.14   937.3 1644.76   952.3 1645.27
   996.9 1646.97  1006.8 1649.51  1026.7 1659.21  1116.2 1708.61  1126.1 1713.52
  1155.9 1725.65  1165.8 1730.72  1195.7 1748.17  1205.6 1752.57  1334.8 1794.63
#Mann= 3 , 0 , 0
    10.1     .08       0   922.3    .045       0   952.3     .08       0
#XS Ineff= 2 , 0
          775.23 1719.24
Permanent Ineff=
       F       F
Bank Sta=922.3,952.3
XS Rating Curve= 0 ,0
Exp/Cntr=0.3,0.1

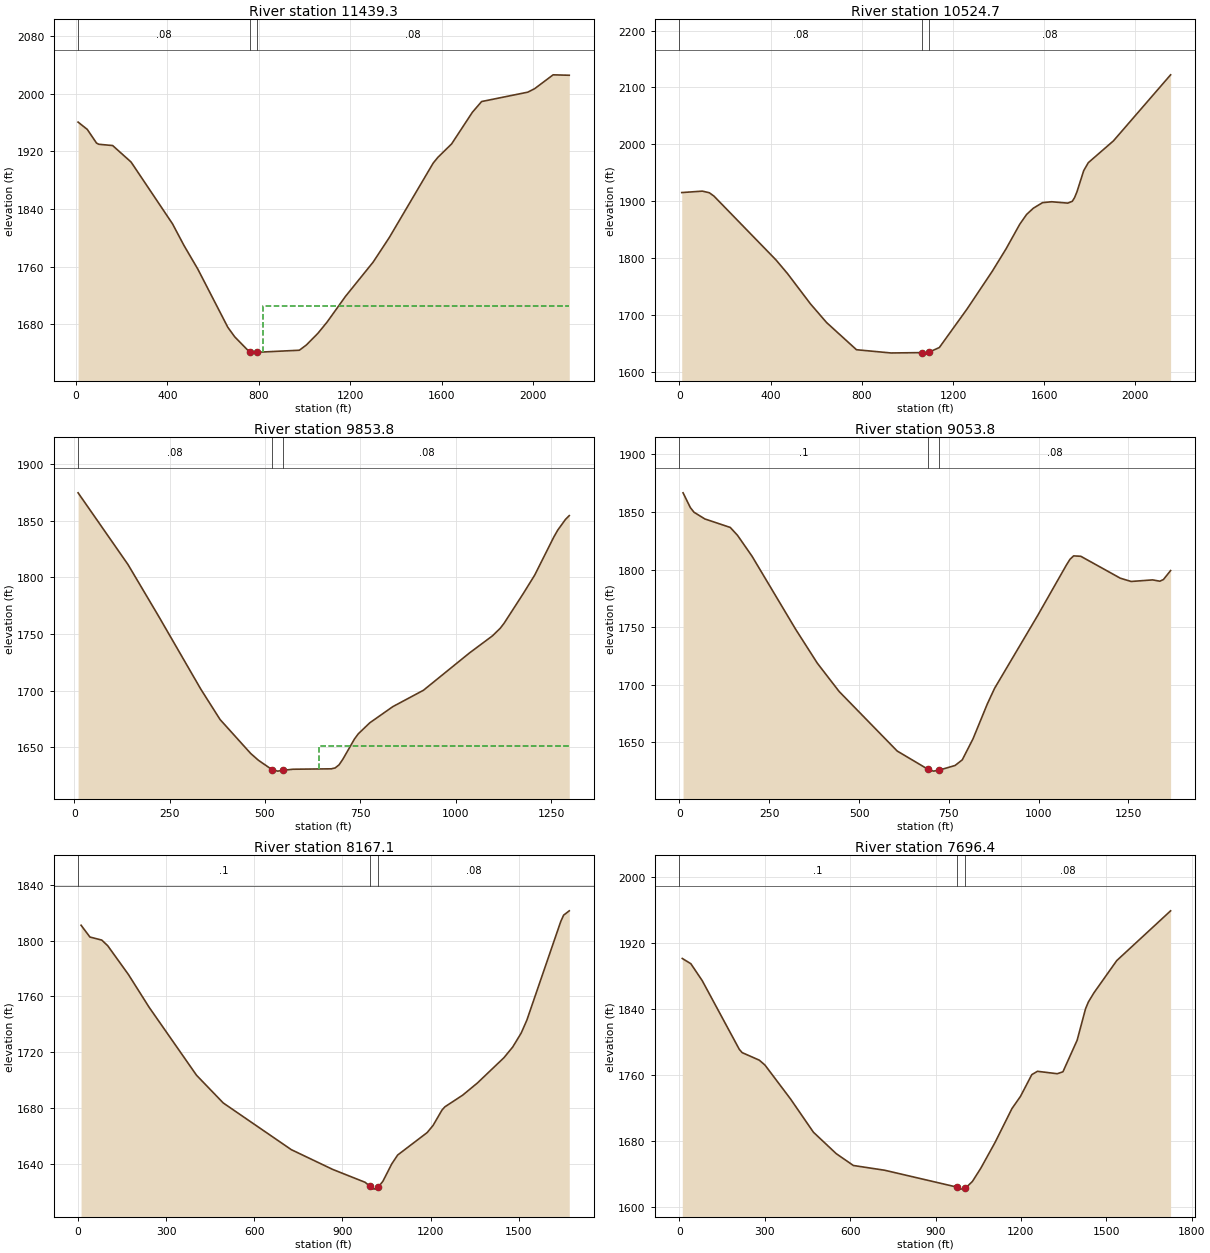
Type RM Length L Ch R = 1 ,11439.3 ,866.7,914.6,961.6
XS GIS Cut Line= 4
     1796860.319      101188.136      1797367.25      101434.701
      1797930.46       101213.44     1798865.246      101534.201
#Sta/Elev= 30
    10.1 1960.45    50.3 1950.31    90.6 1931.41   100.7 1929.72   161.1 1927.97
   241.6 1905.14   422.8 1819.47   473.1 1789.38   533.5 1756.67   664.6 1676.02
   694.8  1662.8   760.5  1641.5   775.5 1640.22   790.5 1641.36   977.2 1644.24
  1007.5 1651.38  1057.9 1667.52  1098.2 1683.15  1178.9 1718.88  1299.9 1766.44
  1370.5 1800.49  1562.1 1903.55  1582.3 1911.45  1642.8 1930.24  1733.6 1974.09
  1773.9 1988.95  1975.6 2001.95  2005.8  2006.8  2086.5 2025.99  2157.1 2025.39
#Mann= 3 , 0 , 0
    10.1     .08       0   760.5    .045       0   790.5     .08       0
#XS Ineff= 2 , 0
                          819.85         1705.82
Permanent Ineff=
       F       F
Bank Sta=760.5,790.5
XS Rating Curve= 0 ,0
Exp/Cntr=0.3,0.1

Type RM Length L Ch R = 1 ,10524.7 ,662.7,670.9,678.9
XS GIS Cut Line= 4
     1796829.874      101325.407     1797364.465      101562.411
     1797725.555      102284.591     1797821.469      103040.624
#Sta/Elev= 30
    10.1 1914.88   100.8 1917.42   131.1 1914.56   151.2 1908.76   423.5 1796.37
   473.9 1772.39   574.7 1719.04   645.3 1686.24   776.5 1638.36   927.9 1632.66
  1064.3 1633.29  1079.3 1632.38  1094.3 1634.03  1139.9 1642.21    1261 1709.72
    1372 1776.35  1432.3 1815.66  1492.5 1859.05  1522.6 1876.35  1552.6 1887.47
  1592.7 1897.17  1632.9 1898.72    1703 1896.32  1723.1 1899.52  1733.1 1906.03
  1743.2 1915.83  1773.2  1953.5  1793.3 1967.47  1903.6 2005.88  2154.3 2122.06
#Mann= 3 , 0 , 0
       0     .08       0  1064.3    .045       0  1094.3     .08       0
Bank Sta=1064.3,1094.3
XS Rating Curve= 0 ,0
Exp/Cntr=0.3,0.1

Type RM Length L Ch R = 1 ,9853.8  ,810.8,800,791.4
XS GIS Cut Line= 3
     1796873.607      101455.212     1796973.153      101989.473
     1797116.215      102730.312
#Sta/Elev= 30
    10.1 1874.69   140.9 1811.37   221.4 1765.62   332.1 1701.14   382.4 1674.45
   462.9 1644.39   483.1 1638.42   518.4 1630.25   533.4 1628.87   548.4 1629.62
   573.6 1630.54   674.2 1630.91   684.3 1631.72   694.4 1634.44   704.4 1639.42
   734.6 1657.17   744.7 1661.78   774.8 1671.51   835.2  1685.8   915.7 1700.31
  1036.4 1733.26  1096.8 1748.41  1116.9 1755.04    1127 1759.43  1177.3 1785.66
  1207.4 1802.04  1257.7 1835.79  1267.8 1841.76  1287.9 1851.13    1298 1854.56
#Mann= 3 , 0 , 0
    10.1     .08       0   518.4    .045       0   548.4     .08       0
#XS Ineff= 2 , 0
                          642.07         1651.12
Permanent Ineff=
       F       F
Bank Sta=518.4,548.4
XS Rating Curve= 0 ,0
Exp/Cntr=0.3,0.1

Type RM Length L Ch R = 1 ,9053.8  ,911.5,886.8,860
XS GIS Cut Line= 3
     1795976.524      101793.734     1796346.885      102408.103
     1796647.926      102984.204
#Sta/Elev= 30
    10.1 1866.69    30.3 1853.91    40.4 1849.87    70.7 1844.02   141.5 1836.63
   161.7  1829.8   202.1 1811.66   323.3 1748.34   383.9 1718.78   444.6 1694.22
   606.2 1642.53   692.3 1626.61   707.3 1625.07   722.3 1625.86   767.4 1629.98
   787.4 1634.87   817.4 1653.17   857.4 1683.59   877.4 1696.98   997.4 1760.23
  1077.4 1804.06  1087.4 1809.03  1097.4 1811.94  1117.4  1811.6  1227.4 1792.57
  1257.4 1789.73  1317.4  1791.1  1337.4 1789.96  1347.4  1791.4  1367.4 1799.19
#Mann= 3 , 0 , 0
       0      .1       0   692.3    .045       0   722.3     .08       0
Bank Sta=692.3,722.3
XS Rating Curve= 0 ,0
Exp/Cntr=0.3,0.1

Type RM Length L Ch R = 1 ,8167.1  ,423.9,470.6,517.4
XS GIS Cut Line= 4
     1795413.141      102170.914     1795677.496      102922.141
     1796336.169      103061.063     1796523.341      103138.056
#Sta/Elev= 30
    10.1 1811.17    40.3 1802.69    80.6  1800.5   100.8 1796.46   171.4 1775.75
   241.9 1752.22   403.2 1703.44     494 1683.57   725.8 1650.02   866.7 1635.84
   977.2 1626.57   992.4 1623.93  1007.4 1621.69  1022.4 1623.35  1037.5 1627.33
  1067.7 1639.81  1087.8 1646.18  1188.2  1662.3  1208.3 1667.42  1238.5 1678.41
  1248.5 1680.78  1308.8 1689.12    1359 1697.85  1449.5 1716.04  1479.2 1723.66
  1508.1 1733.68  1527.4 1742.94    1643 1813.89  1652.7  1818.4  1671.9 1821.51
#Mann= 3 , 0 , 0
       0      .1       0   992.4    .045       0  1022.4     .08       0
Bank Sta=992.4,1022.4
XS Rating Curve= 0 ,0
Exp/Cntr=0.3,0.1

Type RM Length L Ch R = 1 ,7696.4  ,703.1,670.5,637.9
XS GIS Cut Line= 4
     1795258.797      102245.926     1795575.939      102893.931
     1795496.951       103334.01     1795790.337      103807.941
#Sta/Elev= 30
      10 1900.99    40.1 1894.63    80.2 1874.06   210.4 1790.89   220.4 1786.94
   280.6  1777.8   300.6 1771.87   390.8 1730.61   470.9  1690.5   551.1 1664.52
   611.2 1650.23   721.4 1644.45   974.7 1624.07   989.7 1621.59  1004.7 1622.62
  1029.5 1630.88  1059.3 1647.08  1108.9 1678.03  1168.6 1719.24  1198.4  1733.9
  1238.2 1760.26  1258.1 1764.31  1327.8 1761.39  1347.7 1763.74  1397.5 1801.91
  1427.3 1840.29  1437.3 1848.45  1457.2 1859.69  1536.8 1898.44    1726  1958.7
#Mann= 3 , 0 , 0
       0      .1       0   974.7    .045       0  1004.7     .08       0
Bank Sta=974.7,1004.7
XS Rating Curve= 0 ,0
Exp/Cntr=0.3,0.1

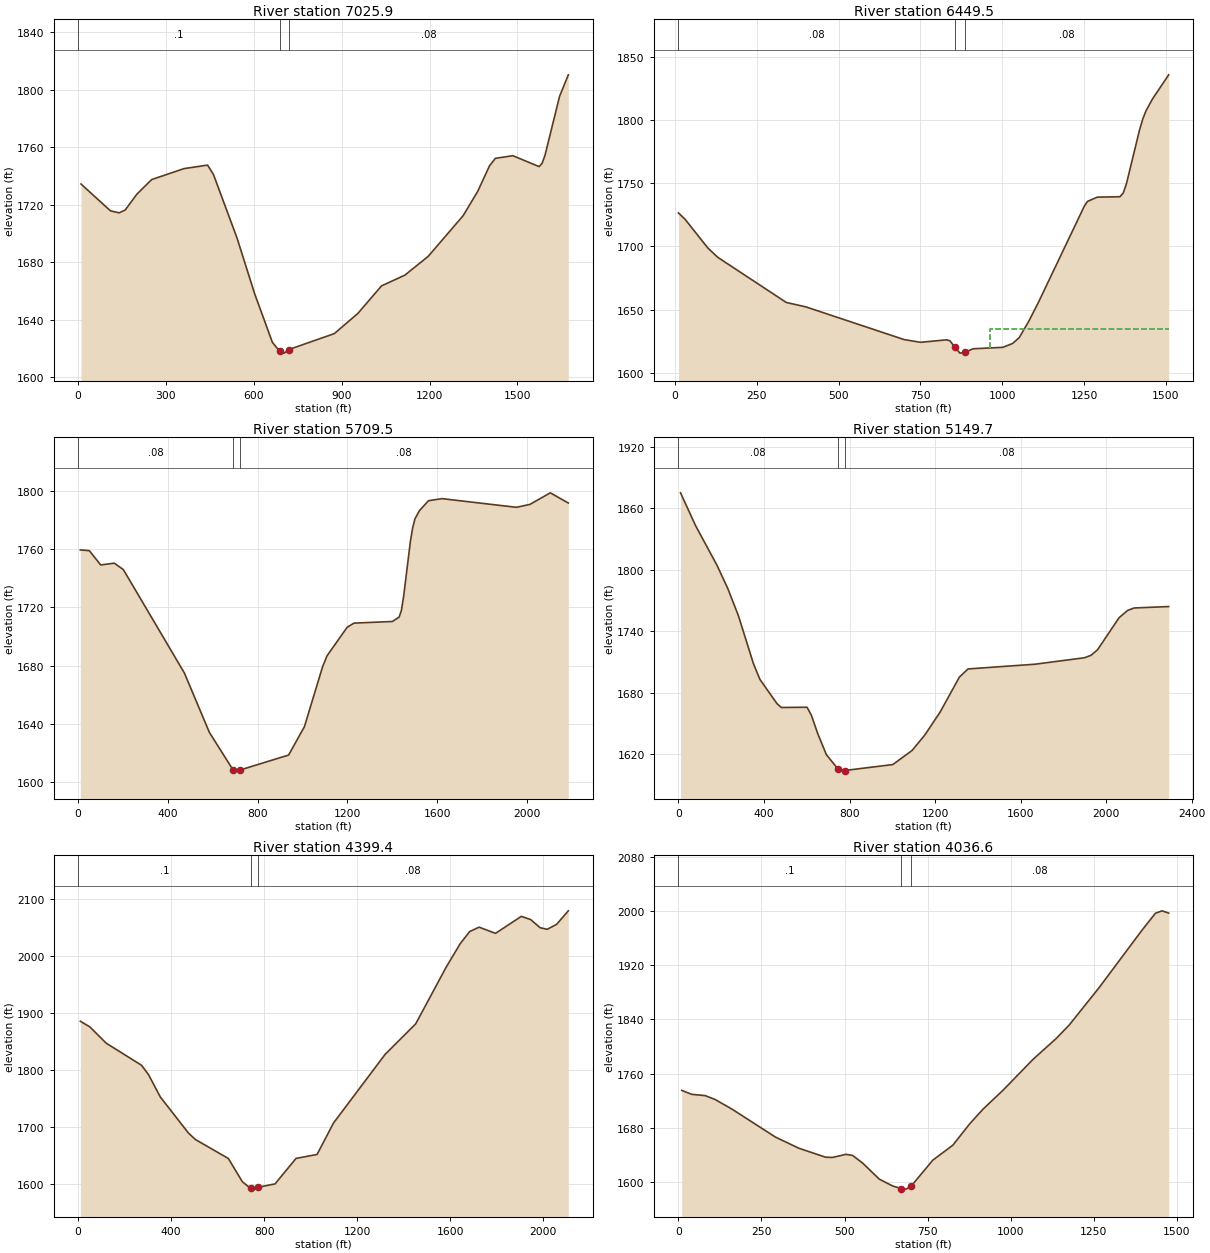
Type RM Length L Ch R = 1 ,7025.9  ,591.4,576.4,561.5
XS GIS Cut Line= 4
      1794337.99      102785.483     1794876.327      102854.437
     1795259.986      103164.749     1795429.247      103779.731
#Sta/Elev= 30
    10.1 1734.53   110.6 1715.86   140.7 1714.47   160.8 1716.41     201 1727.47
   251.3  1737.6   361.8 1745.23   442.2 1747.67   462.3 1741.15   542.7 1697.02
   603.2 1658.07   663.6 1624.39   688.9 1618.07   703.9  1616.9   718.9 1619.34
   875.1 1630.48   955.6 1644.54  1036.2 1663.66  1115.9 1671.14  1195.6  1684.2
  1315.2 1712.57  1365.1 1729.59  1404.9 1747.14  1424.9 1752.37  1484.7  1754.2
  1574.4 1746.61  1584.3 1748.85  1594.3 1754.41  1644.1 1795.45    1674 1810.45
#Mann= 3 , 0 , 0
       0      .1       0   688.9    .045       0   718.9     .08       0
Bank Sta=688.9,718.9
XS Rating Curve= 0 ,0
Exp/Cntr=0.3,0.1

Type RM Length L Ch R = 1 ,6449.5  ,722.1,740,755.6
XS GIS Cut Line= 4
     1794357.194      102820.601     1794839.945      103483.579
     1795097.413      103531.855     1795406.283      103826.218
#Sta/Elev= 30
      10 1726.52      30  1721.6     100 1698.76     130 1691.44     340 1655.65
   400.1 1652.15   700.1  1626.3   750.1 1624.17   830.2 1626.12   840.3 1625.29
   855.5 1620.22   870.5  1615.6   885.5 1616.24   910.8 1619.05  1001.5 1620.18
  1031.7 1623.24  1051.8 1627.83  1082.1 1641.29  1111.8 1656.41  1250.8 1731.83
  1260.7 1735.61  1290.4 1738.97  1359.9  1739.3  1369.8 1742.24  1379.7 1749.64
  1419.4 1791.85  1429.4 1800.72  1439.3 1807.22  1459.1 1816.57  1508.7 1835.72
#Mann= 3 , 0 , 0
      10     .08       0   855.5    .045       0   885.5     .08       0
#XS Ineff= 2 , 0
                          961.56         1634.77
Permanent Ineff=
       F       F
Bank Sta=855.5,885.5
XS Rating Curve= 0 ,0
Exp/Cntr=0.3,0.1

Type RM Length L Ch R = 1 ,5709.5  ,579.2,559.8,542.7
XS GIS Cut Line= 4
     1794206.871      102877.027     1794216.209      103350.936
     1794515.237      103757.163     1795592.866      104298.798
#Sta/Elev= 30
    10.1 1759.36    50.4 1758.86   100.9 1749.07   161.4 1750.28   201.7 1745.92
     474 1674.88     585 1634.26     691 1608.35     706 1607.63     721 1608.36
   938.1 1618.65  1008.6  1638.1    1089 1678.94  1109.1 1686.68  1199.5 1706.39
  1229.7 1709.17  1400.6 1710.28  1430.7 1713.34  1440.8 1717.89  1450.8 1727.62
    1481 1765.38    1491 1774.58  1501.1 1780.66  1521.2 1786.33  1561.4 1793.13
  1621.7 1794.55  1953.3  1788.6  2013.6 1790.61  2104.1 1798.54  2184.5 1791.55
#Mann= 3 , 0 , 0
       0     .08       0     691    .045       0     721     .08       0
Bank Sta=691,721
XS Rating Curve= 0 ,0
Exp/Cntr=0.3,0.1

Type RM Length L Ch R = 1 ,5149.7  ,722.2,750.3,777.2
XS GIS Cut Line= 4
     1793543.462      103684.349     1793945.391      103948.992
     1794650.646      104044.906     1795700.064      104372.144
#Sta/Elev= 30
      10 1875.12    80.2 1843.09   180.5 1804.31   230.6 1781.82   280.7 1755.03
   350.9  1708.2     381 1692.92   461.2 1669.14   481.2 1665.45   601.5 1665.68
   621.6 1657.97   651.6 1639.84   691.7 1619.41   746.9 1605.14   761.9 1603.28
   776.9 1603.88  1002.5  1609.7  1092.7 1623.49  1152.9 1638.78  1223.2 1660.81
    1314 1695.19  1354.3  1703.1    1667  1707.7  1898.9 1714.04  1929.2 1716.43
  1959.4 1721.75  2060.3 1753.12  2100.6 1760.28  2130.9 1762.65  2292.2 1764.03
#Mann= 3 , 0 , 0
       0     .08       0   746.9    .045       0   776.9     .08       0
Bank Sta=746.9,776.9
XS Rating Curve= 0 ,0
Exp/Cntr=0.3,0.1

Type RM Length L Ch R = 1 ,4399.4  ,368.5,362.8,357.6
XS GIS Cut Line= 4
     1793144.348      104013.148     1793685.858      104236.736
     1793883.329       104609.11     1794763.486      105269.228
#Sta/Elev= 30
    10.1 1885.51    50.5 1875.78   121.2 1847.06   272.7 1808.57     303 1792.05
   353.5 1753.03   474.7 1689.73     505 1678.36   646.1 1645.26   706.3 1604.56
   741.5 1592.91   756.5 1591.61   771.5 1594.66   846.8 1600.75   937.1 1645.42
  1027.5 1652.33  1098.2 1707.41  1320.2 1827.68  1451.5 1881.03  1582.7 1980.46
  1643.2 2021.63  1683.6 2042.59    1724 2050.29  1794.6 2039.44  1905.7 2069.24
    1946 2063.49  1986.4 2049.28  2016.7 2046.55  2057.1 2055.18  2107.5 2078.88
#Mann= 3 , 0 , 0
       0      .1       0   741.5    .045       0   771.5     .08       0
Bank Sta=741.5,771.5
XS Rating Curve= 0 ,0
Exp/Cntr=0.3,0.1

Type RM Length L Ch R = 1 ,4036.6  ,335.6,324.3,313
XS GIS Cut Line= 4
     1792969.844      104221.539     1793377.061      104464.039
     1793711.071      104880.407     1794072.533      105177.812
#Sta/Elev= 30
    10.1 1735.19    40.3 1729.35    80.7 1727.47   110.9 1721.65   161.3 1707.55
   292.4  1666.2     363 1649.75   443.7 1636.52   463.9 1636.29   504.2 1640.81
   524.3 1639.21   554.5 1627.96   604.9 1604.16   645.2 1594.08   670.5 1590.32
   685.5 1589.48   700.5 1593.79     766  1632.3   826.5  1654.5   876.8 1685.82
   917.1 1707.58   977.5 1735.58  1067.5 1780.98  1137.2 1811.74    1177 1831.95
  1266.7    1887  1396.1 1971.99    1436 1996.58  1455.9 2000.17  1475.8 1996.82
#Mann= 3 , 0 , 0
       0      .1       0   670.5    .045       0   700.5     .08       0
Bank Sta=670.5,700.5
XS Rating Curve= 0 ,0
Exp/Cntr=0.3,0.1

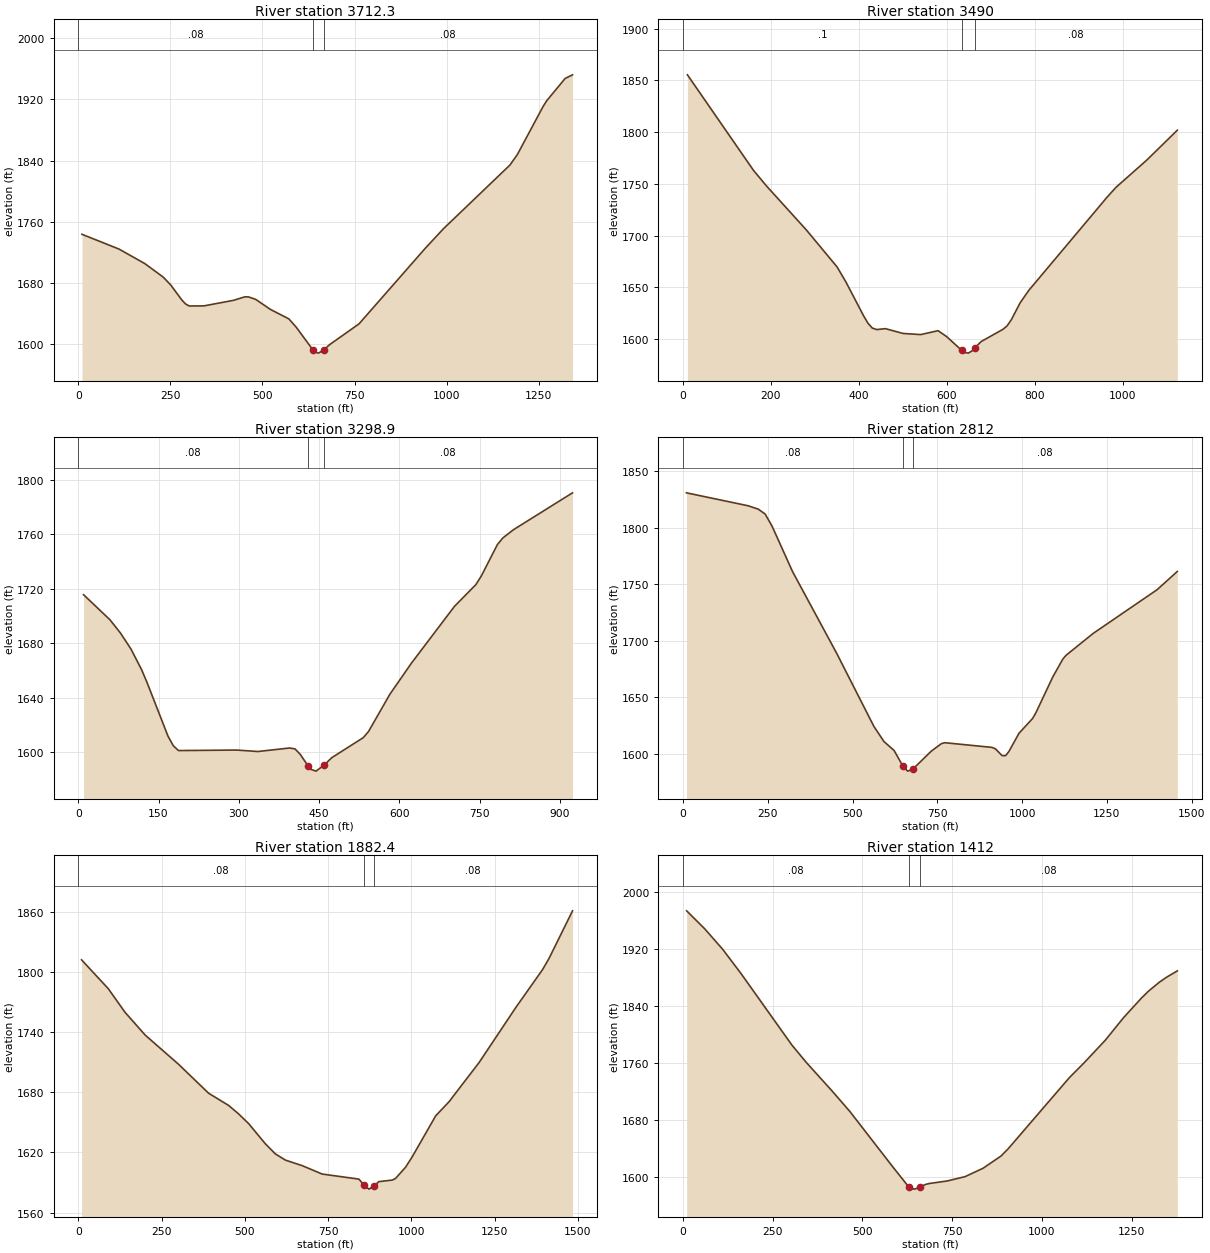
Type RM Length L Ch R = 1 ,3712.3  ,226,222.3,218.7
XS GIS Cut Line= 3
     1792732.354      104547.047     1793324.619      104885.598
     1793900.255      105207.166
#Sta/Elev= 30
      10 1743.54   110.4 1724.26   180.6 1705.25   230.7 1687.48   250.8 1677.38
   280.9 1657.74   290.9 1652.57     301 1649.77   341.1 1649.89   421.4 1657.14
   451.5 1661.63   461.5 1661.71   481.6 1658.41   521.7 1645.26   571.8 1632.84
   591.9 1621.86   637.1 1592.24   642.1 1589.67   652.1  1588.1   667.1 1592.64
   682.2 1599.18   762.1 1626.38   941.9 1725.22   991.9 1751.13  1171.7 1834.11
  1191.7 1847.72  1261.6 1910.61  1271.6 1918.29  1321.6 1947.38  1341.6 1952.11
#Mann= 3 , 0 , 0
       0     .08       0   637.1    .045       0   667.1     .08       0
Bank Sta=637.1,667.1
XS Rating Curve= 0 ,0
Exp/Cntr=0.3,0.1

Type RM Length L Ch R = 1 ,3490    ,194.8,191.1,187.3
XS GIS Cut Line= 4
     1792584.321      104923.547     1793123.083       105037.37
     1793322.274       105120.84     1793663.742      105227.075
#Sta/Elev= 30
      10 1855.36   160.2 1763.06   190.2 1747.76   280.3 1705.53   350.4 1669.65
   370.4 1655.22   410.5 1622.58   420.5 1615.31   430.5 1610.55   440.5 1609.12
   460.5 1609.99   500.6 1605.34   540.6 1604.25   580.1 1608.02   599.7 1602.26
   633.8 1589.03     639 1587.18   648.8 1586.33   658.6  1588.8   663.8 1591.48
   678.3 1597.58   727.4 1609.27   737.2  1612.7     747 1618.81   766.6 1634.86
   786.5 1647.02   965.3 1737.48   985.2 1746.78  1054.7  1772.9  1124.2 1801.82
#Mann= 3 , 0 , 0
       0      .1       0   633.8    .045       0   663.8     .08       0
Bank Sta=633.8,663.8
XS Rating Curve= 0 ,0
Exp/Cntr=0.3,0.1

Type RM Length L Ch R = 1 ,3298.9  ,502.7,486.9,471.2
XS GIS Cut Line= 5
     1792830.938       105005.12      1793059.65      105141.627
     1793142.543      105252.968     1793274.847      105289.677
     1793654.257      105327.618
#Sta/Elev= 30
     9.9 1715.64    59.2 1697.22    78.9 1687.45    98.6 1675.65   118.4  1660.5
   128.2 1651.44   167.7 1611.68   177.6 1604.58   187.4 1601.04   296.1 1601.41
   335.8 1600.34   395.2 1602.93   405.2 1602.24     415 1598.22   429.4 1589.81
   434.6 1587.22   444.4 1585.92   459.4 1590.32   473.8  1595.8   532.7 1610.53
   542.5 1615.04   582.6 1642.55   622.7 1665.29     703 1706.99   743.1 1723.04
   753.2 1729.31   783.3 1752.44   793.3 1757.26   813.4 1763.41   923.8 1790.53
#Mann= 3 , 0 , 0
       0     .08       0   429.4    .045       0   459.4     .08       0
Bank Sta=429.4,459.4
XS Rating Curve= 0 ,0
Exp/Cntr=0.3,0.1

Type RM Length L Ch R = 1 ,2812    ,891.9,929.6,964.2
XS GIS Cut Line= 4
     1792504.153      105986.704     1792845.194      105810.863
      1793443.25      105658.528     1793879.491      105522.837
#Sta/Elev= 30
    10.1 1830.63   191.9 1819.21   222.1 1816.22   242.3 1811.87   262.5  1801.3
   323.1 1761.07   453.4 1688.86   562.9 1624.47   592.7 1611.07   622.6 1603.17
   647.4 1589.94   662.4 1584.98   677.4 1586.63   732.1 1602.61     762 1609.23
   771.9 1610.07   911.3 1605.93   921.2 1604.67   941.1 1598.66   951.1 1598.58
     961 1602.28   990.9 1618.41  1030.7 1631.36  1040.6 1636.44  1090.2 1667.93
    1120 1683.85    1130  1687.3  1209.4 1706.49  1398.1 1745.11  1457.7 1761.21
#Mann= 3 , 0 , 0
       0     .08       0   647.4    .045       0   677.4     .08       0
Bank Sta=647.4,677.4
XS Rating Curve= 0 ,0
Exp/Cntr=0.3,0.1

Type RM Length L Ch R = 1 ,1882.4  ,478.1,470.4,462.6
XS GIS Cut Line= 3
     1792494.005      106139.432     1793093.444      106194.522
     1793702.784      106832.072
#Sta/Elev= 30
      10 1811.83    90.3 1783.05   140.5 1759.55   200.7 1736.95     301 1707.82
   391.3 1678.96   451.5 1666.77   481.6  1658.3   511.7 1648.62   561.8 1628.53
   591.9 1618.45     622  1612.3   672.1 1606.82   732.2 1598.41   842.5 1593.37
   857.6 1587.49   872.6 1583.39   887.6 1586.43   902.6 1590.87   942.7  1592.4
   952.7 1594.06   982.8 1605.29  1002.8  1615.7    1073 1656.37  1113.1 1670.45
  1203.3 1709.48  1313.5 1764.31  1393.7    1802  1413.7 1813.47  1483.9 1860.68
#Mann= 3 , 0 , 0
       0     .08       0   857.6    .045       0   887.6     .08       0
Bank Sta=857.6,887.6
XS Rating Curve= 0 ,0
Exp/Cntr=0.3,0.1

Type RM Length L Ch R = 1 ,1412    ,441.7,447.4,453.1
XS GIS Cut Line= 4
     1792379.609      106404.039     1792814.278      106619.086
     1793239.797      106884.463     1793587.533      107062.907
#Sta/Elev= 30
    10.1 1973.45    60.6 1948.18   111.1 1919.17   161.7 1885.48   303.1 1785.49
   343.5 1760.95   414.2 1721.59   464.8 1692.27   585.3 1614.05   625.4 1588.73
   630.4 1586.61   635.4 1584.49   645.4 1583.33   660.4 1586.16   675.5 1589.86
   685.6 1591.16   735.7 1594.71   785.9 1600.82     836 1612.58   886.1 1629.73
   906.2 1639.99  1076.6 1739.63  1116.7 1759.91  1176.9 1792.19    1227 1823.38
  1277.1    1851  1297.1 1860.89  1327.2 1873.36  1347.2 1880.33  1377.3 1889.25
#Mann= 3 , 0 , 0
       0     .08       0   630.4    .045       0   660.4     .08       0
Bank Sta=630.4,660.4
XS Rating Curve= 0 ,0
Exp/Cntr=0.3,0.1

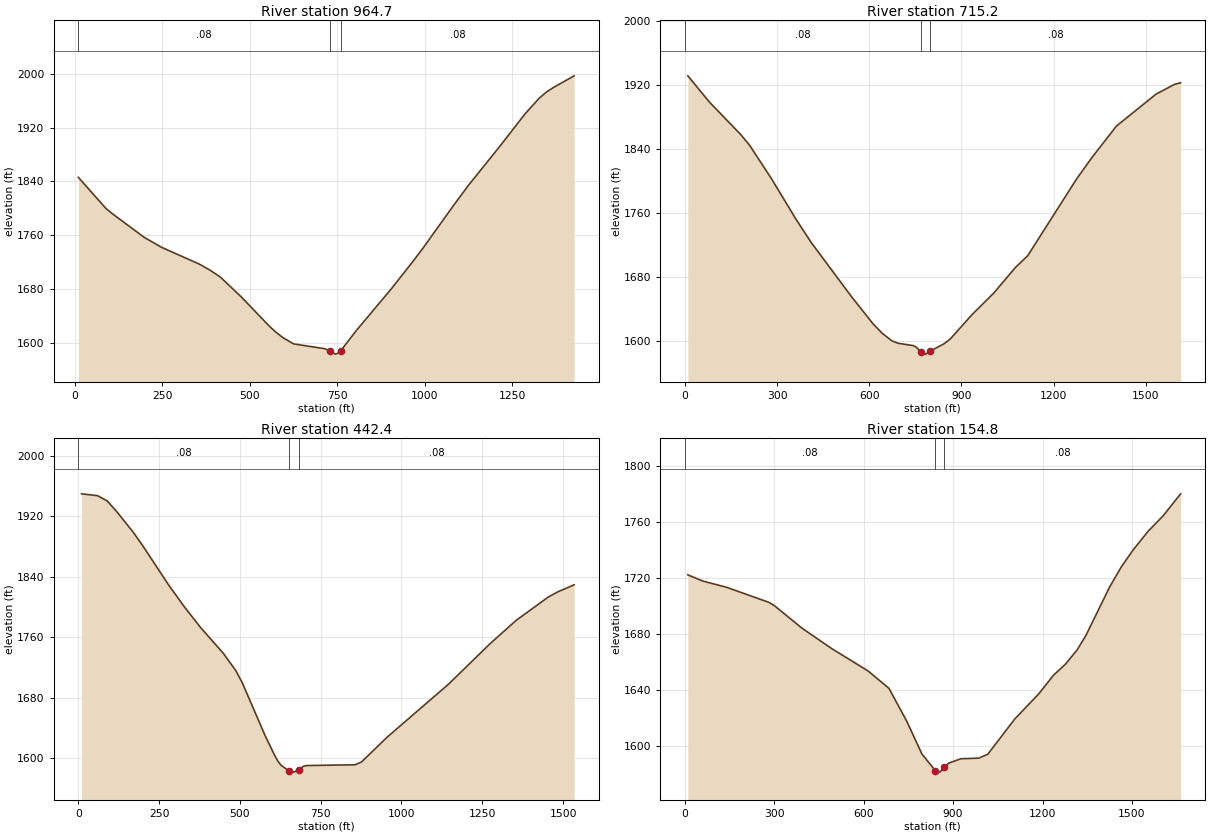
Type RM Length L Ch R = 1 ,964.7   ,244.6,249.5,254.4
XS GIS Cut Line= 4
       1792166.5      106791.244     1792568.411      106896.501
     1792966.459      107259.167     1793406.741      107431.285
#Sta/Elev= 30
     9.9  1846.2      89 1799.81   108.8 1791.43   197.8 1757.08   247.3 1742.23
   356.1 1717.03   385.8 1708.29   415.5 1697.97   475.3 1668.52   555.1 1625.14
     575 1615.71     595 1607.68   624.9 1598.54   714.6 1591.31   729.5 1587.56
  744.44  1583.3   754.5 1585.23   759.5 1588.14   804.4 1618.47   904.1 1680.34
     964 1719.79   994.2 1740.53  1084.7 1806.27  1124.9 1834.46  1215.5 1893.09
  1285.9 1940.21  1326.1 1963.48  1346.2 1972.49  1366.3 1979.42  1426.7 1997.11
#Mann= 3 , 0 , 0
     9.9     .08       0   729.5    .045       0   759.5     .08       0
Bank Sta=729.5,759.5
XS Rating Curve= 0 ,0
Exp/Cntr=0.3,0.1

Type RM Length L Ch R = 1 ,715.2   ,282.1,272.7,264.1
XS GIS Cut Line= 4
     1791996.504      106814.314     1792513.926      107142.257
     1792827.294      107535.789      1793300.99      107688.829
#Sta/Elev= 30
      10 1930.86    80.3 1897.97   180.8 1857.97   210.9 1844.08   281.2 1802.83
   361.5 1751.89   411.7 1722.39   542.3    1655   612.6 1620.96   642.8    1609
     673 1599.96   693.1 1596.74   743.4 1593.71   753.5  1591.7   768.6 1585.57
   773.6 1583.59   783.6 1583.07   798.6 1586.82     844 1596.13   864.1 1602.06
   934.6 1632.38    1005  1659.2  1075.4 1691.16  1115.7 1705.93  1274.9 1801.94
  1324.7 1828.64  1404.4    1868  1533.8 1908.07  1593.5 1920.14  1613.5 1922.22
#Mann= 3 , 0 , 0
       0     .08       0   768.6    .045       0   798.6     .08       0
Bank Sta=768.6,798.6
XS Rating Curve= 0 ,0
Exp/Cntr=0.3,0.1

Type RM Length L Ch R = 1 ,442.4   ,296.2,287.6,278.3
XS GIS Cut Line= 4
     1791901.737      107029.129     1792232.666      107331.282
     1792696.687      107640.629      1793182.29      107849.259
#Sta/Elev= 30
      10 1949.62    59.7 1947.14    89.6 1940.16   119.5  1925.8   169.3 1899.18
   199.2 1881.09   278.8 1829.52   328.6 1799.92   378.4  1772.8   448.1 1739.05
     488 1715.38   507.9 1699.24   577.6 1630.31   607.5  1603.8   617.4 1596.19
   627.4 1590.55   652.2 1583.24   667.2  1581.6   682.2 1585.02   697.1 1589.38
     707 1590.29   856.4 1591.35   876.3 1595.06     956    1628  1145.4 1697.85
    1275 1751.82  1354.8  1782.3  1454.5 1813.21  1484.5  1820.2  1534.3 1829.33
#Mann= 3 , 0 , 0
       0     .08       0   652.2    .045       0   682.2     .08       0
Bank Sta=652.2,682.2
XS Rating Curve= 0 ,0
Exp/Cntr=0.3,0.1

Type RM Length L Ch R = 1 ,154.8   ,173.9,154.8,135.8
XS GIS Cut Line= 4
     1791631.957      107331.282      1792178.71      107673.003
     1792685.896       107834.87     1793160.707      107939.185
#Sta/Elev= 30
    10.1 1722.06    60.4 1717.64     141 1713.12   282.1 1702.44   302.2 1699.82
   392.9 1684.05   493.6 1669.34   614.5 1653.55   684.9 1641.08   745.2 1617.36
   795.4 1594.26   840.7 1582.34   855.7 1581.31   870.7 1584.87   885.8 1587.74
     926 1590.85   986.3  1591.3  1016.4 1594.07  1106.8  1619.2  1187.1 1637.08
  1236.7 1650.41  1276.4 1658.19    1316 1668.48  1345.8 1678.91  1425.2 1713.39
  1464.9 1727.95  1504.5 1739.98  1554.1 1753.14  1603.8 1763.96  1663.3 1779.86
#Mann= 3 , 0 , 0
       0     .08       0   840.7    .045       0   870.7     .08       0
Bank Sta=840.7,870.7
XS Rating Curve= 0 ,0
Exp/Cntr=0.3,0.1

Chan Stop Cuts=-1
Use User Specified Reach Order=0